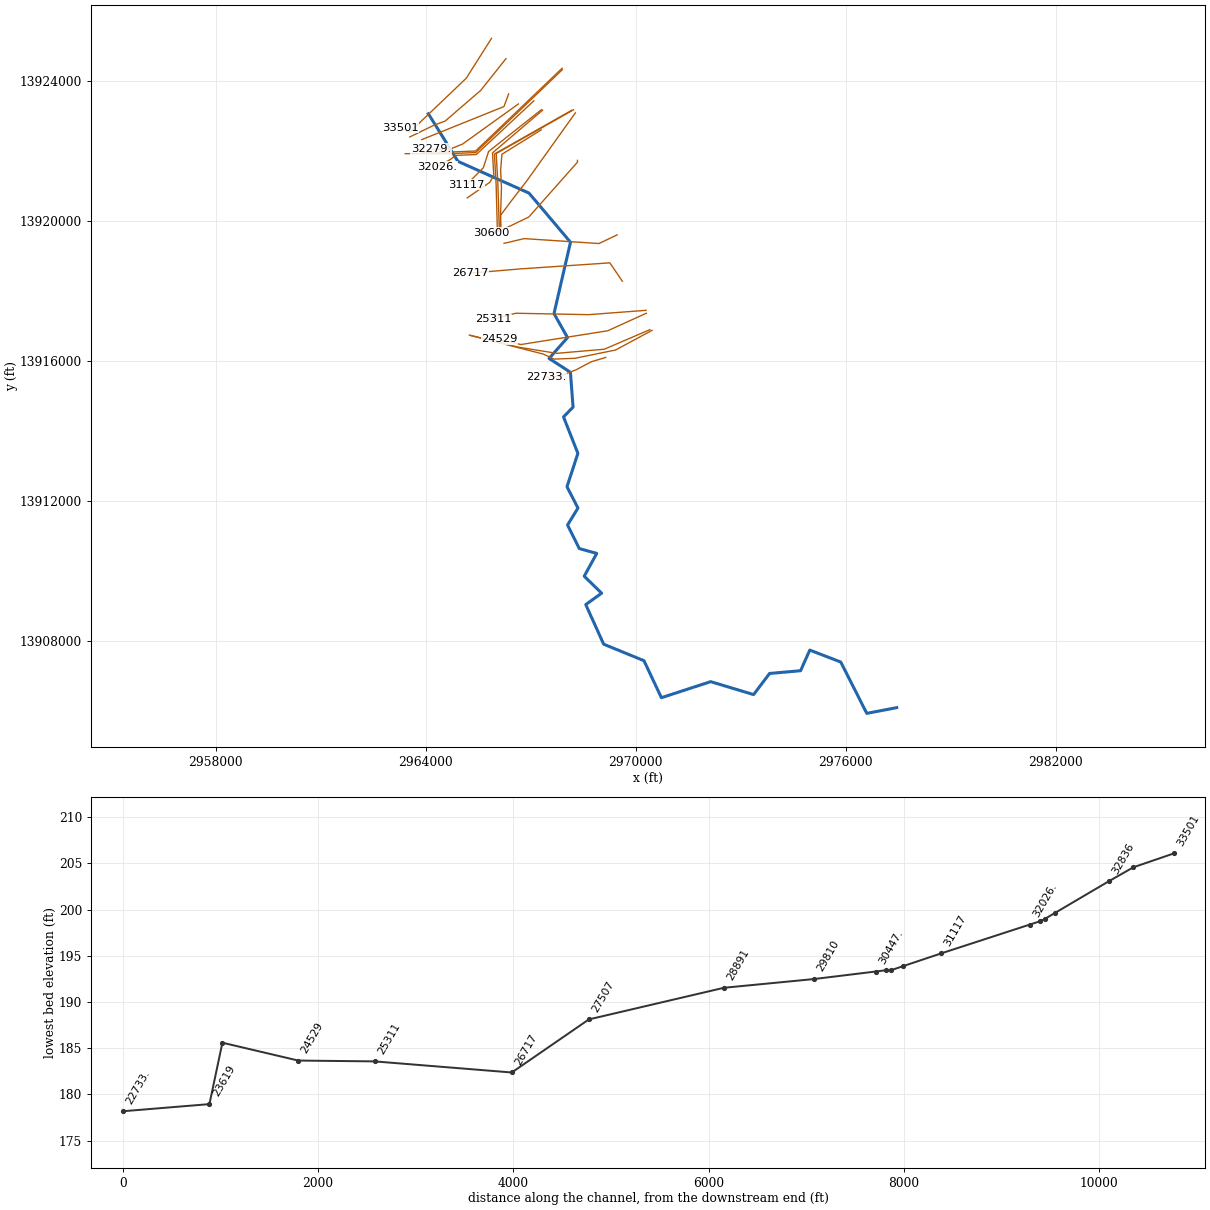
--- K160-00-00.prj (project) ---

Proj Title=K160-00-00
Current Plan=p07
Default Exp/Contr=0.3,0.1
English Units
Geom File=g02
Flow File=f07
Flow File=f06
Plan File=p07
Plan File=p06
Y Axis Title=Elevation
X Axis Title(PF)=Main Channel Distance
X Axis Title(XS)=Station
BEGIN DESCRIPTION:
Cypress Creek Watershed
Rock Hollow
HCFCD Unit K160-00-00
Flood Hazard Model
10, 2, 1, 0.2%
Filename K160-00-00
Prepared by:  Halff Associates Inc  DATE:  3-26-04
Reviewed by:  _____________________  DATE:  __________________
STATUS (Final)
TROPICAL STORM ALLISON RECOVERY PROJECT
END DESCRIPTION:
DSS File=dss
DSS Export Rating Curves= 0
DSS Export Rating Curve Sorted= 0
DSS Export Volume Flow Curves= 0
DXF OffsetX= 0
DXF OffsetY= 0
DXF ScaleX= 1
DXF ScaleY= 10

--- K160-00-00.p07 (plan) ---

Plan Title=Effective FW 2013
Program Version=3.13
Short Identifier=Eff FW 2013
Geom File=g02
Flow File=f07
Subcritical Flow
K Sum by GR= 0
Std Step Tol= 0.01
Critical Tol= 0.01
Num of Std Step Trials= 20
Max Error Tol= 0.3
Flow Tol Ratio= 0.001
Split Flow NTrial= 30
Split Flow Tol= 0.02
Split Flow Ratio= 0.02
Log Output Level= 0
Friction Slope Method= 1
Unsteady Friction Slope Method= 2
Unsteady Bridges Friction Slope Method= 1
Parabolic Critical Depth
Global Vel Dist= 0 , 0 , 0
Global Log Level= 0
CheckData=True
Encroach Param=-1 ,0,0, 2
Encroach River=K160-00-00
Encroach Reach=K160-00-00_0043
Encroach Node=33501
       1  4983.3  5038.1
Encroach Node=33086
       1  4983.3 5262.01
Encroach Node=32836
       1 4871.46  5038.1
Encroach Node=32279.
       1 4953.98    5050
Encroach Node=32176
       1    4775    5100
Encroach Node=32131
       1    4775    5100
Encroach Node=32026.
       1    4750    5050
Encroach Node=31117
       1  4971.3  5067.7
Encroach Node=30721.
       1 4971.03    5023
Encroach Node=30600
       1  4973.8  5017.1
Encroach Node=30547
       1  4973.8  5017.1
Encroach Node=30447.
       1    4970    5040
Encroach Node=29810
       1    4908  5054.4
Encroach Node=28891
       1  4842.2  5042.1
Encroach Node=27507
       1  3595.5 6007.89
Encroach Node=26717
       1 3510.31 6379.18
Encroach Node=25311
       1 3911.17 6208.62
Encroach Node=24529
       1  4153.5 5941.06
Encroach Node=23752
       1 3297.48 6036.41
Encroach Node=23619
       1    3715  5024.1
Encroach Node=22733.
       1  4959.3  5069.3
Encroach Node=22538
       1  4958.4  5093.9
Encroach Node=22093
       1  4958.4  5093.9
Encroach Node=21647
       1  4966.8  5168.1
Encroach Node=20316
       1  4980.8  5026.7
Encroach Node=19879
       1  4975.2  5021.1
Encroach Node=19811
       1  4975.2  5021.1
Encroach Node=19715.
       1    4980    5020
Encroach Node=18950
       1  4958.5 5023.55
Encroach Node=17940
       1  4941.8    5026
Encroach Node=16783
       1 4854.79  5036.7
Encroach Node=15648
       1    4950 5081.84
Encroach Node=14389
       1  4974.1  5043.8
Encroach Node=13172
       1    4750    5063
Encroach Node=12257
       1 4527.63  5030.4
Encroach Node=10949
       1 4878.62  5036.7
Encroach Node=9235
       1    4000    5300
Encroach Node=8596.
       1 3924.65    5150
Encroach Node=8494
       1    3900  5068.1
Encroach Node=8460
       1 3924.65  5068.1
Encroach Node=8261.
       1    4100  5068.1
Encroach Node=7467
       1    4200  5064.5
Encroach Node=6253
       1    4400    5053
Encroach Node=4642
       1 4879.19  5065.3
Encroach Node=4335
       1  4950.7 5334.95
BEGIN DESCRIPTION:
FEMA Effective Floodway October 2013
Flows based on the revised Modified-Puls data in conjunction with the Cypress Creek LOMR.
END DESCRIPTION:
Computation Interval=1HOUR
Output Interval=1HOUR
Run HTab= 0
Run UNet= 0
Run PostProcess= 0
UNET Theta= 1
UNET Theta Warmup= 1
UNET ZTol= 0.02
UNET ZSATol= 0.05
UNET MxIter= 20
UNET MaxInSteps= 0
UNET DtIC= 0
UNET DtMin= 0
UNET MaxCRTS= 20
UNET WFStab= 2
UNET SFStab= 1
UNET WFX= 1
UNET SFX= 1
UNET DSS MLevel= 4
UNET DZMax Abort= 100
UNET Convert EG Bridges=-1
UNET Use Existing IB Tables=-1
UNET Froude Reduction=False
UNET Froude Limit= 1
UNET Froude Power= 10
Instantaneous Interval=1HOUR
Write IC File= 0
IC Time=0,,
Echo Input=False
Echo Output=False
Write Detailed= 0
Detailed Automatic Start=False, 10

--- K160-00-00.p06 (plan) ---

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Plan Title=Effective MP 2013
Short Identifier=Eff MP 2013
Geom File=g02
Flow File=f06
Encroach Param=-1 ,0,0, 0
FEMA Effective MP 2013

--- K160-00-00.f07 (steady flow) ---

Flow Title=Effective FW 2013
Program Version=3.13
Number of Profiles= 2
Profile Names=1PCT_100yr,1PCTFloodway_10
River Rch & RM=K160-00-00,K160-00-00_0043       ,33501
     514     514
River Rch & RM=K160-00-00,K160-00-00_0043       ,33086
     545     545
River Rch & RM=K160-00-00,K160-00-00_0043       ,32279.
     584     584
River Rch & RM=K160-00-00,K160-00-00_0043       ,31117
     632     632
River Rch & RM=K160-00-00,K160-00-00_0043       ,30721.
     670     670
River Rch & RM=K160-00-00,K160-00-00_0043       ,29810
     708     708
River Rch & RM=K160-00-00,K160-00-00_0043       ,28891
     766     766
River Rch & RM=K160-00-00,K160-00-00_0043       ,23752
     209     209
River Rch & RM=K160-00-00,K160-00-00_0043       ,22733.
     234     234
River Rch & RM=K160-00-00,K160-00-00_0043       ,22093
     254     254
River Rch & RM=K160-00-00,K160-00-00_0043       ,20316
     287     287
River Rch & RM=K160-00-00,K160-00-00_0043       ,19879
     303     303
River Rch & RM=K160-00-00,K160-00-00_0043       ,18950
     325     325
River Rch & RM=K160-00-00,K160-00-00_0043       ,17940
     357     357
River Rch & RM=K160-00-00,K160-00-00_0043       ,16783
     397     397
River Rch & RM=K160-00-00,K160-00-00_0043       ,15648
     441     441
River Rch & RM=K160-00-00,K160-00-00_0043       ,14389
     495     495
River Rch & RM=K160-00-00,K160-00-00_0043       ,13172
     554     554
River Rch & RM=K160-00-00,K160-00-00_0043       ,12257
     602     602
River Rch & RM=K160-00-00,K160-00-00_0043       ,10949
     679     679
River Rch & RM=K160-00-00,K160-00-00_0043       ,9235
    1624    1624
River Rch & RM=K160-00-00,K160-00-00_0043       ,8261.
    1722    1722
River Rch & RM=K160-00-00,K160-00-00_0043       ,6253
    1847    1847
River Rch & RM=K160-00-00,K160-00-00_0043       ,4642
    2062    2062
Boundary for River Rch & Prof#=K160-00-00,K160-00-00_0043       , 1
Up Type= 0
Dn Type= 1
Dn Known WS=161.47
Boundary for River Rch & Prof#=K160-00-00,K160-00-00_0043       , 2
Up Type= 0
Dn Type= 1
Dn Known WS=162.47
DSS Import GetInterval= 0
DSS Import GetPeak= 0
DSS Import FillOption= 0

--- K160-00-00.f06 (steady flow) ---

Flow Title=Effective MP 2013
Program Version=3.13
Number of Profiles= 4
Profile Names=10PCT_10yr,2PCT_50yr,1PCT_100yr,0.2PCT_500yr
River Rch & RM=K160-00-00,K160-00-00_0043       ,33501
     181     382     514     971
River Rch & RM=K160-00-00,K160-00-00_0043       ,33086
     192     404     545    1028
River Rch & RM=K160-00-00,K160-00-00_0043       ,32279.
     206     434     584    1103
River Rch & RM=K160-00-00,K160-00-00_0043       ,31117
     222     469     632    1194
River Rch & RM=K160-00-00,K160-00-00_0043       ,30721.
     236     497     670    1265
River Rch & RM=K160-00-00,K160-00-00_0043       ,29810
     249     526     708    1337
River Rch & RM=K160-00-00,K160-00-00_0043       ,28891
     270     569     766    1447
River Rch & RM=K160-00-00,K160-00-00_0043       ,23752
      53      99     209     835
River Rch & RM=K160-00-00,K160-00-00_0043       ,22733.
      63     117     234     854
River Rch & RM=K160-00-00,K160-00-00_0043       ,22093
      71     132     254     869
River Rch & RM=K160-00-00,K160-00-00_0043       ,20316
      86     157     287     890
River Rch & RM=K160-00-00,K160-00-00_0043       ,19879
      93     171     303     901
River Rch & RM=K160-00-00,K160-00-00_0043       ,18950
     104     189     325     914
River Rch & RM=K160-00-00,K160-00-00_0043       ,17940
     120     216     357     931
River Rch & RM=K160-00-00,K160-00-00_0043       ,16783
     141     253     397     951
River Rch & RM=K160-00-00,K160-00-00_0043       ,15648
     165     294     441     972
River Rch & RM=K160-00-00,K160-00-00_0043       ,14389
     197     348     495     995
River Rch & RM=K160-00-00,K160-00-00_0043       ,13172
     234     410     554    1018
River Rch & RM=K160-00-00,K160-00-00_0043       ,12257
     266     463     602    1036
River Rch & RM=K160-00-00,K160-00-00_0043       ,10949
     319     552     679    1061
River Rch & RM=K160-00-00,K160-00-00_0043       ,9235
     685    1271    1624    2754
River Rch & RM=K160-00-00,K160-00-00_0043       ,8261.
     738    1350    1722    2915
River Rch & RM=K160-00-00,K160-00-00_0043       ,6253
     807    1450    1847    3117
River Rch & RM=K160-00-00,K160-00-00_0043       ,4642
     928    1624    2062    3465
Boundary for River Rch & Prof#=K160-00-00,K160-00-00_0043       , 1
Up Type= 0
Dn Type= 3
Dn Slope=0.0016
Boundary for River Rch & Prof#=K160-00-00,K160-00-00_0043       , 2
Up Type= 0
Dn Type= 3
Dn Slope=0.0016
Boundary for River Rch & Prof#=K160-00-00,K160-00-00_0043       , 3
Up Type= 0
Dn Type= 3
Dn Slope=0.0016
Boundary for River Rch & Prof#=K160-00-00,K160-00-00_0043       , 4
Up Type= 0
Dn Type= 3
Dn Slope=0.0016
DSS Import GetInterval= 0
DSS Import GetPeak= 0
DSS Import FillOption= 0

--- K160-00-00.g02 (geometry) ---

Geom Title=K160-00-00 2013
Program Version=3.13

River Reach=K160-00-00      ,K160-00-00_0043
Reach XY= 30
      2964079.44     13923056.95      2964922.56     13921697.05
      2966954.04     13920788.04      2968138.42     13919385.08
      2967667.36     13917345.44       2968053.7     13916659.09
      2967526.35     13916063.27      2968137.03     13915667.78
      2968211.25     13914671.69      2967939.25       13914392.
      2968349.72     13913349.57      2968037.85     13912396.29
      2968351.22     13911788.66      2968055.21     13911301.68
      2968390.28     13910628.93      2968888.25       13910491.
      2968530.04       13909839.       2969028.3     13909353.76
      2968574.31     13909028.24      2969085.59     13907896.29
       2970237.5     13907424.07      2970734.25       13906367.
      2972141.15     13906825.11      2973367.71     13906456.19
      2973824.31     13907059.49      2974709.73     13907138.48
      2974972.75     13907727.89       2975857.3     13907385.88
      2976600.35     13905918.86      2977454.54      13906082.7

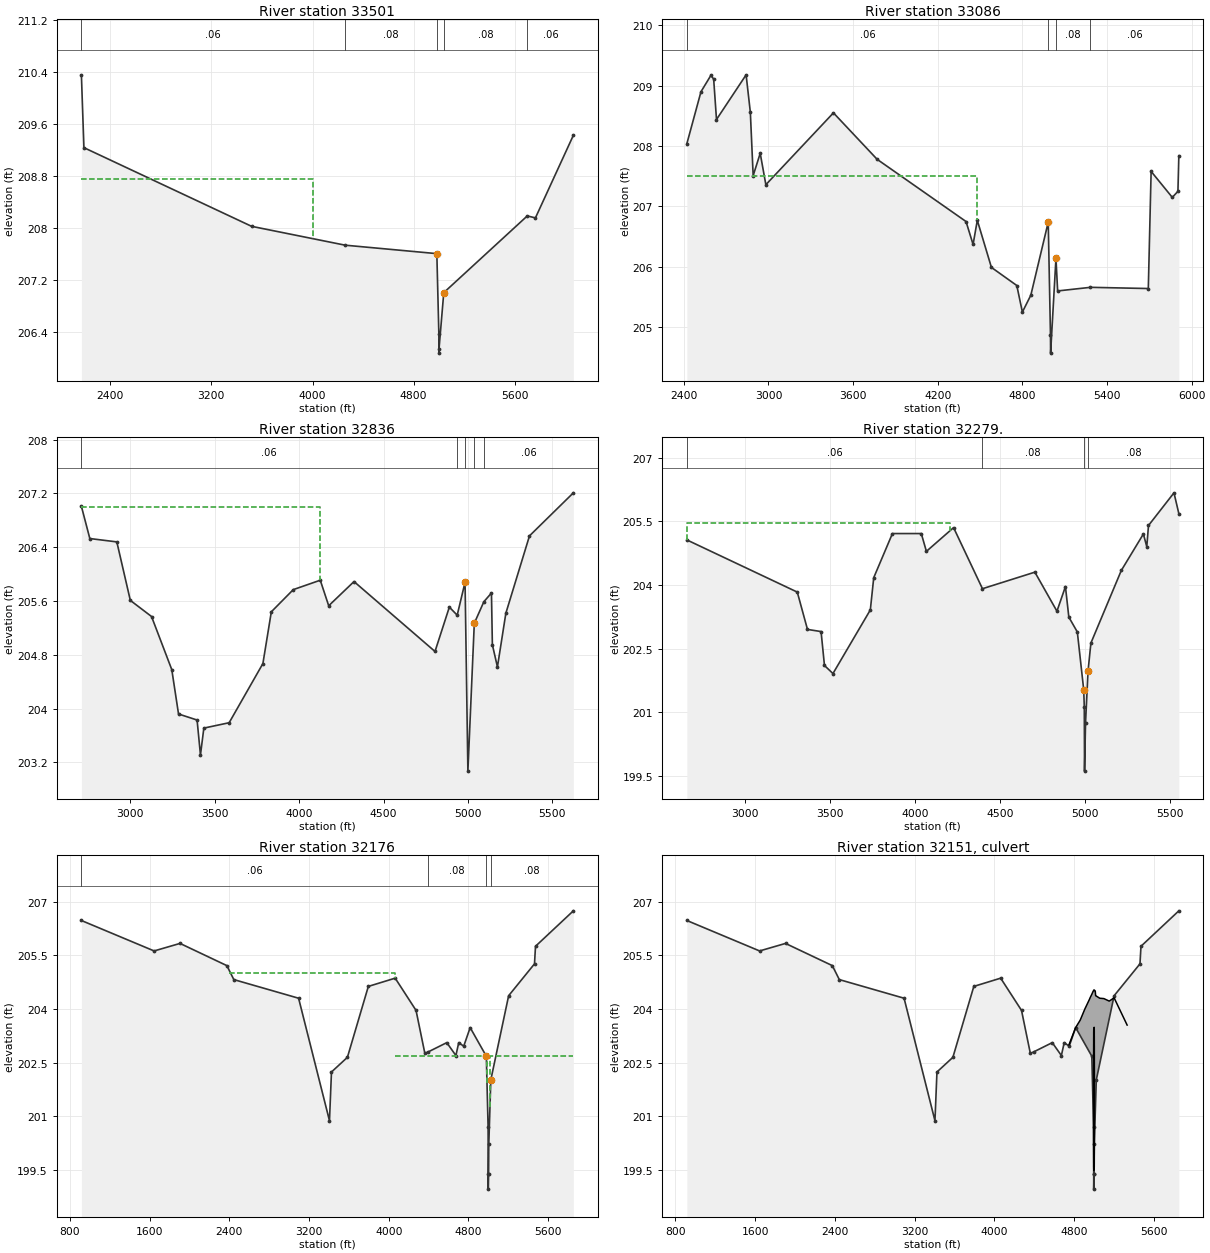
Type RM Length L Ch R = 1 ,33501   ,494.4,415,345.7
BEGIN DESCRIPTION:
INTERP_XS2
END DESCRIPTION:
XS GIS Cut Line= 4
 2965883.033103313925212.0622289      2965163.24      13924074.4
      2963540.42     13922523.87 2963273.037711613922659.9192257
#Sta/Elev= 12
  2172.3  210.35  2192.3  209.23  3518.5  208.02  4258.5  207.73  4983.3   207.6
  4999.2  206.37  5000.1  206.07  5000.8  206.14  5038.1     207  5698.5  208.18
    5763  208.15    6063  209.42
#Mann= 5 ,-1 , 0
  2172.3     .06       0  4258.5     .08       0  4983.3     .06       0
  5038.1     .08       0  5698.5     .06       0
#XS Ineff= 2 , 0
       0    4000  208.75               0
Permanent Ineff=
       F       F
Bank Sta=4983.3,5038.1
Exp/Cntr=0.3,0.1

Type RM Length L Ch R = 1 ,33086   ,283.9,250,249
BEGIN DESCRIPTION:
INTERP_XS1.5
END DESCRIPTION:
XS GIS Cut Line= 5
      2966294.82     13924630.47      2965573.57     13923723.09
      2964559.16     13922848.27      2964247.39     13922731.94
      2963548.48     13922393.73
#Sta/Elev= 30
  2421.4  208.04  2521.4   208.9  2591.4  209.17  2611.4  209.11  2631.4  208.44
  2841.4  209.18  2871.4  208.56  2891.4  207.51  2941.4  207.88  2981.4  207.36
  3460.5  208.55  3770.5  207.78  4400.5  206.75  4450.5  206.37  4480.5  206.77
  4580.5  205.99  4760.5  205.69    4800  205.25    4860  205.53  4983.3  206.74
  4999.2  204.87  5000.1  204.57  5038.1  206.14    5050   205.6  5282.8  205.66
  5692.8  205.64  5712.8  207.58  5862.8  207.15  5902.8  207.25  5909.3  207.84
#Mann= 4 ,-1 , 0
  2421.4     .06       0  4983.3     .06       0  5038.1     .08       0
  5282.8     .06       0
#XS Ineff= 2 , 0
       0  4480.5   207.5               0
Permanent Ineff=
       F       F
Bank Sta=4983.3,5038.1
Exp/Cntr=0.3,0.1

Type RM Length L Ch R = 1 ,32836   ,558,557,538.4
BEGIN DESCRIPTION:
Cross Section K160-00-00-X19
END DESCRIPTION:
XS GIS Cut Line= 3
      2966372.27      13923623.1      2966237.57     13923261.71
      2963890.5313922316.9323627
#Sta/Elev= 30
  2709.5  207.01  2759.5  206.53  2919.5  206.48  2999.5  205.61  3125.2  205.37
  3245.2  204.58  3285.2  203.92  3395.2  203.83  3415.2  203.31  3435.2  203.71
  3585.2  203.79  3785.2  204.67  3835.2  205.44  3965.2  205.77  4125.2  205.91
  4175.2  205.53  4325.2  205.89  4805.2  204.85  4890.2  205.51  4936.7  205.39
  4983.3  205.88  5000.1  203.07  5038.1  205.27  5094.8  205.59  5139.8  205.72
  5145.2  204.95  5175.2  204.62  5225.2  205.42  5365.2  206.57  5625.2  207.21
#Mann= 5 ,-1 , 0
  2709.5     .06       0  4936.7     .08       0  4983.3     .06       0
  5038.1     .08       0  5094.8     .06       0
#XS Ineff= 2 , 0
       0  4125.2     207               0
Permanent Ineff=
       F       F
Bank Sta=4983.3,5038.1
Exp/Cntr=0.3,0.1

Type RM Length L Ch R = 1 ,32279.  ,218.6,103,79.9
BEGIN DESCRIPTION:
Mound - XS4
END DESCRIPTION:
XS GIS Cut Line= 4
      2966651.04      13923337.3      2965052.87     13922188.13
      2964654.57     13922028.99      2964156.22     13922047.55
#Sta/Elev= 30
    2658  205.06    3308  203.83    3368  202.95    3448   202.9    3468   202.1
    3518  201.91    3738  203.41    3758  204.17    3868  205.21    4038  205.21
    4068  204.79    4228  205.35    4398  203.91  4706.5   204.3  4836.5  203.38
  4886.5  203.96  4906.5  203.24  4956.5  202.89 4994.02  201.53 4997.45  201.13
 4998.92  199.61 5004.82  200.74 5019.54  201.97  5036.5  202.63  5215.4  204.34
  5345.4   205.2  5365.4   204.9  5375.4   205.4  5525.4  206.17  5554.1  205.68
#Mann= 4 ,-1 , 0
    2658     .06       0    4398     .08       0 4994.02     .08       0
 5019.54     .08       0
#XS Ineff= 2 , 0
       0    4208  205.45               0
Permanent Ineff=
       F       F
Bank Sta=4994.02,5019.54
Exp/Cntr=0.5,0.3

Type RM Length L Ch R = 1 ,32176   ,60.6,45,44
BEGIN DESCRIPTION:
Upstream Section of Bridge/Culvert/Weir
END DESCRIPTION:
XS GIS Cut Line= 5
      2967898.16      13924356.7      2965429.41      13921992.1
      2964827.16      13921968.5      2964680.96      13921958.1
      2963910.97      13921959.8
#Sta/Elev= 30
   915.2  206.47  1645.2  205.62  1905.2  205.83  2375.2  205.21  2445.2  204.82
  3095.2   204.3  3405.2  200.88  3425.2  202.24  3585.2  202.65  3795.2  204.63
  4064.7  204.86    4274  203.96  4362.5  202.76    4395   202.8  4582.5  203.06
    4674   202.7  4702.5  203.06  4752.5  202.96  4817.2  203.48  4979.5  202.68
  4997.2   200.7  4998.6   199.4  4998.7  198.97  5001.4  199.38  5004.2  200.22
  5024.5  202.02  5203.4  204.37    5463  205.26    5473  205.75    5853  206.74
#Mann= 4 ,-1 , 0
   915.2     .06       0    4395     .08       0  4979.5     .08       0
  5024.5     .08       0
#XS Ineff= 3 ,-1
    2400  4064.7     205  4064.7  4986.5   202.7  5016.1    5853   202.7
Permanent Ineff=
       F       F       F
Bank Sta=4979.5,5024.5
Exp/Cntr=0.5,0.3

Type RM Length L Ch R = 2 ,32151   ,,,
BEGIN DESCRIPTION:
MOUND
Structure ID: K160-00-00-S4
END DESCRIPTION:
Bridge Culvert--1,0,-1,-1, 0
Deck Dist Width WeirC Skew NumUp NumDn MinLoCord MaxHiCord MaxSubmerge Is_Ogee
10,30,2.6,0, 24, 24, , , 0.95, 0, ,,,
    4750  4817.2  4863.2  4909.7    4956  4961.8  4979.5  4993.7  4997.2  4998.6
  4998.7  4999.8  5001.4  5002.3  5004.2  5013.7    5014  5017.9  5024.5  5059.2
  5100.3  5154.1  5203.4    5334
     203  203.48  203.69     204  204.27  204.31  204.41   204.5  204.51  204.52
  204.52  204.52  204.53  204.53  204.53   204.5   204.5  204.37  204.36   204.3
  204.29  204.22  204.31  203.55
                                                                                
                                                                                
                                
    4750  4817.2  4863.2  4909.7    4956  4961.8  4979.5  4993.7  4997.2  4998.6
  4998.7  4999.8  5001.4  5002.3  5004.2  5013.7    5014  5017.9  5024.5  5059.2
  5100.3  5154.1  5203.4    5334
     203  203.48  203.69     204  204.27  204.31  204.41   204.5  204.51  204.52
  204.52  204.52  204.53  204.53  204.53   204.5   204.5  204.37  204.36   204.3
  204.29  204.22  204.31  203.55
                                                                                
                                                                                
                                
BR Coef= 1 , 1 , 1 ,1.25, 0 ,,,0.8,0,2,0,
WSPro=,,,, 1 ,,,, 0 ,,,, 0 ,,,,-1 ,-1 ,-1 , 0 , 0 , 0 , 0 , 0
Culvert=1,4,,30,0.015,0.5,1,1,3,199.48,4998.5,199.34,4998.5,Culvert #1  , 0 ,10
Culvert Bottom n=0.015
Culvert=1,4,,30,0.015,0.5,1,1,3,199.5,5004.1,199.38,5004.1,Culvert #2  , 0 ,10
Culvert Bottom n=0.015
BC Design=,, 0 ,, 0 ,,,,,,
BC HTab HWMax=205.16

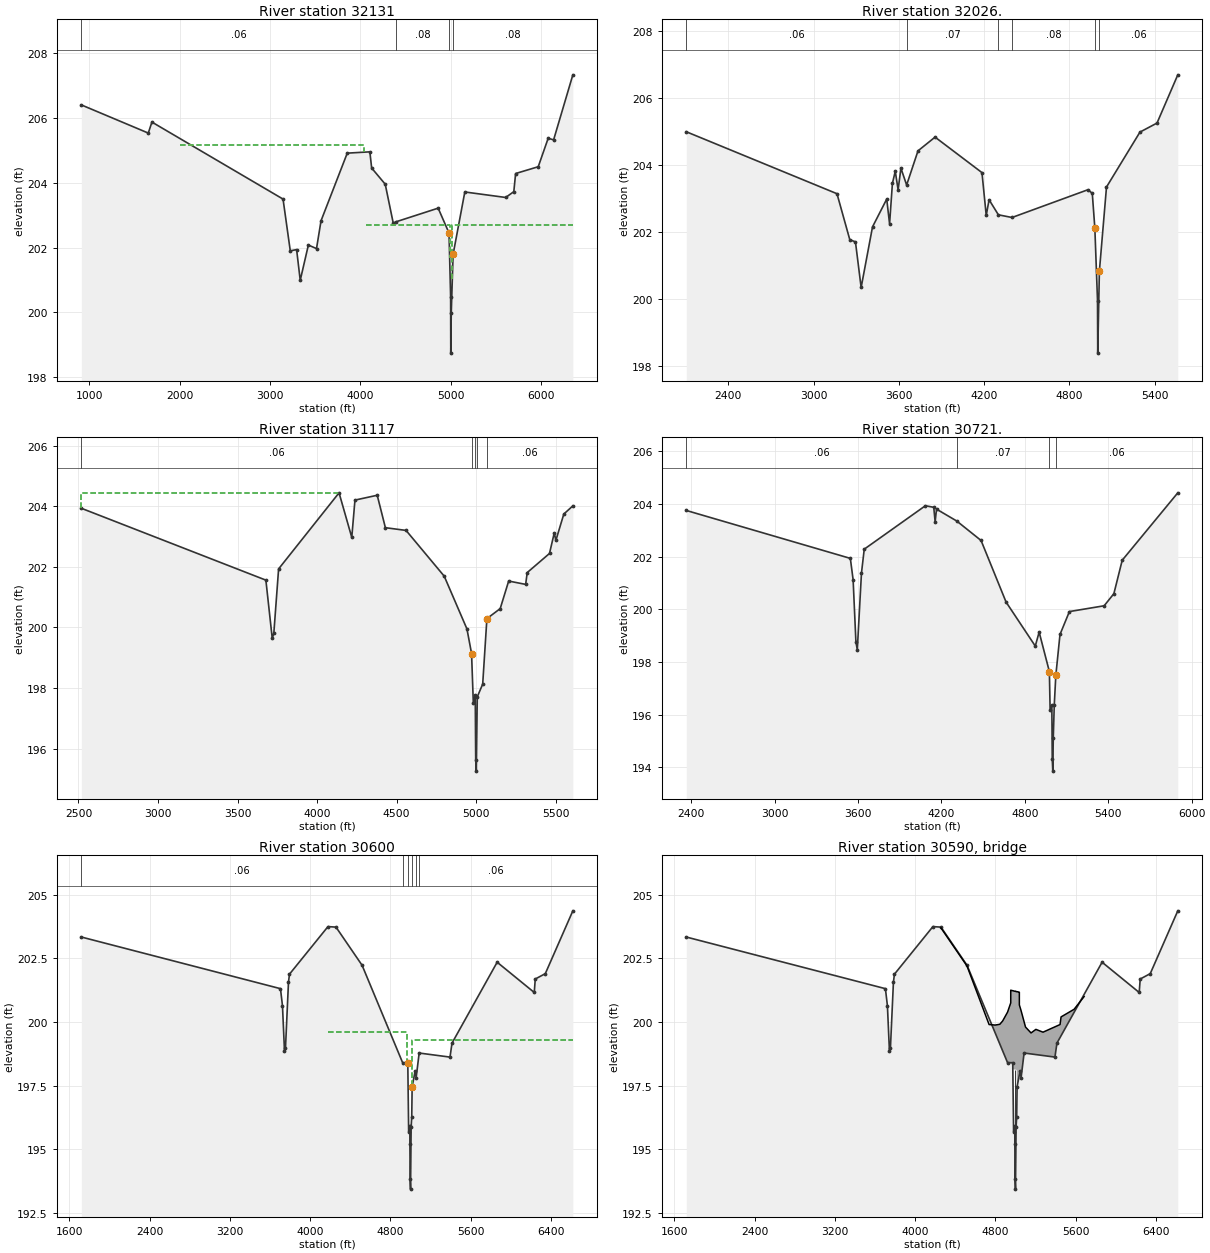
Type RM Length L Ch R = 1 ,32131   ,103.2,105,151.4
BEGIN DESCRIPTION:
Downstream Section of Bridge/Culvert/Weir
END DESCRIPTION:
XS GIS Cut Line= 5
      2967902.54       13924313.      2965432.42      13921947.1
      2964828.36      13921923.5      2964682.06       13921913.
      2963419.24      13921915.8
#Sta/Elev= 30
   914.2  206.41  1654.2  205.54  1694.2  205.88  3144.2   203.5  3224.2   201.9
  3294.2  201.94  3334.2  200.99  3424.2  202.08  3514.2  201.97  3564.2  202.83
  3854.2  204.92    4104  204.96    4124  204.46    4274  203.96  4362.5  202.76
    4395   202.8  4859.3  203.22  4979.5  202.45  4997.2  200.47  4998.7  198.74
  5004.2  199.99  5024.5  201.79  5154.1  203.72  5605.8  203.55  5695.8  203.73
  5715.8  204.29  5965.8   204.5  6075.8  205.38  6135.8  205.33  6348.6  207.34
#Mann= 4 ,-1 , 0
   914.2     .06       0    4395     .08       0  4979.5     .08       0
  5024.5     .08       0
#XS Ineff= 3 ,-1
    2000    4034  205.16  4057.2  4986.5   202.7  5016.1  6348.6   202.7
Permanent Ineff=
       F       F       F
Bank Sta=4979.5,5024.5
Exp/Cntr=0.5,0.3

Type RM Length L Ch R = 1 ,32026.  ,523.5,909,910
BEGIN DESCRIPTION:
Mound - XS1
END DESCRIPTION:
XS GIS Cut Line= 5
      2967092.04      13923427.3      2965447.58     13921890.78
      2964872.57     13921867.69      2964679.74     13921732.59
      2964329.88     13921546.69
#Sta/Elev= 30
  2104.5  204.99  3164.5  203.14  3254.5  201.77  3294.5   201.7  3334.5  200.34
  3414.5  202.15  3514.5  202.98  3534.5  202.24  3554.5  203.45  3574.5  203.81
  3594.5  203.26  3614.5   203.9  3654.5   203.4  3734.5  204.42  3854.5  204.83
  4184.5  203.77  4214.5  202.49  4234.5  202.96    4300  202.51    4396  202.43
  4930.6  203.26  4960.6  203.15 4978.65  202.11 4997.37  199.95 4998.96  198.38
  5010.6  200.83  5060.6  203.34    5296  204.98    5416  205.25  5562.2  206.69
#Mann= 6 ,-1 , 0
  2104.5     .06       0  3654.5     .07       0    4300     .06       0
    4396     .08       0 4978.65     .08       0  5010.6     .06       0
#XS Ineff= 2 , 0
       0  3854.5  204.83               0
Permanent Ineff=
       F       F
Bank Sta=4978.65,5010.6
Exp/Cntr=0.3,0.1

Type RM Length L Ch R = 1 ,31117   ,360.3,396,427.4
BEGIN DESCRIPTION:
INTERP_XS1
END DESCRIPTION:
XS GIS Cut Line= 4
      2967306.83     13923172.27      2965799.73      13921978.1
      2965648.47     13921511.72      2965169.92     13921033.17
#Sta/Elev= 30
  2518.2  203.93  3678.2  201.56  3718.2  199.64  3728.2  199.81  3758.2  201.93
  4138.2  204.44  4218.2  202.97  4238.2   204.2  4378.2  204.36  4429.5  203.29
  4559.5   203.2  4799.5  201.69  4942.3  199.95  4971.3  199.14  4982.3  197.52
  4994.4  197.76  4997.3  195.64  5001.2  195.26  5007.2  197.71  5041.3  198.13
  5067.7  200.29  5151.3  200.62  5204.6  201.53  5311.3  201.42  5321.3  201.81
  5461.3  202.44  5491.3  203.12  5501.3  202.87  5551.3  203.74  5608.1  204.01
#Mann= 5 ,-1 , 0
  2518.2     .06       0  4971.3     .08       0  4994.4     .07       0
  5007.2     .08       0  5067.7     .06       0
#XS Ineff= 2 , 0
       0  4138.2  204.44               0
Permanent Ineff=
       F       F
Bank Sta=4971.3,5067.7
Exp/Cntr=0.3,0.1

Type RM Length L Ch R = 1 ,30721.  ,78.3,121,200.7
BEGIN DESCRIPTION:
Warren Ranch Rd (2) - XS4
END DESCRIPTION:
XS GIS Cut Line= 5
       2967340.9      13923158.6      2965911.02     13921937.46
       2965947.5     13921290.65      2965831.41     13921094.94
      2965189.92     13920651.59
#Sta/Elev= 30
  2364.8  203.76  3544.8  201.94  3564.8  201.13  3584.8  198.77  3594.8  198.47
  3624.8  201.38  3644.8  202.29  4084.8  203.94  4144.8  203.88  4154.8  203.33
  4164.8  203.81    4310  203.36  4485.2  202.62  4665.2  200.28  4875.2  198.61
    4903  199.14 4976.59  197.64  4981.9  196.18 4994.25  196.36 4997.22  194.32
  5001.2  193.86 5004.52   195.1 5011.67  196.36    5023   197.5    5053  199.05
  5120.6  199.92  5370.6  200.14  5440.6   200.6  5500.6  201.87  5900.4  204.43
#Mann= 4 ,-1 , 0
  2364.8     .06       0    4310     .07       0 4976.59     .06       0
    5023     .06       0
#XS Ineff= 2 , 0
       0  3644.8  202.29               0
Permanent Ineff=
       F       F
Bank Sta=4976.59,5023
Exp/Cntr=0.5,0.3

Type RM Length L Ch R = 1 ,30600   ,62.5,53,51.6
BEGIN DESCRIPTION:
Upstream Section of Bridge/Culvert/Weir
END DESCRIPTION:
XS GIS Cut Line= 5
      2968174.75     13923156.45      2965966.41     13921906.45
      2966015.46     13921000.28      2966049.52     13919745.99
 2965868.637199313919660.6296124
#Sta/Elev= 30
  1719.5  203.34  3704.4  201.31  3724.4  200.64  3744.4  198.87  3754.4  198.97
  3784.4  201.57  3794.4  201.88    4178  203.75    4258  203.73    4518  202.23
  4922.3   198.4  4973.8   198.4  4982.3  195.69  4994.4  195.93  4994.7  195.22
  4997.3  193.81  5001.2  193.43  5007.2  195.88  5013.1  196.26  5017.1  197.45
  5047.1  198.08  5057.1  197.81  5087.1  198.78  5394.6  198.62  5414.6  199.17
  5864.6  202.35  6234.6  201.16  6244.6  201.69  6344.6   201.9  6619.3  204.37
#Mann= 6 ,-1 , 0
  1719.5     .06       0  4922.3     .07       0  4973.8     .06       0
  5017.1     .06       0  5057.1     .08       0  5087.1     .06       0
#XS Ineff= 3 ,-1
    3000  3784.4  201.57    4179 4970.21   199.6 5017.84  6619.3   199.3
Permanent Ineff=
       F       T       F
Bank Sta=4973.8,5017.1
Exp/Cntr=0.5,0.3

Type RM Length L Ch R = 3 ,30590   ,,,
BEGIN DESCRIPTION:
WARREN RANCH RD (2)
Structure ID: K160-00-00-S2
END DESCRIPTION:
Bridge Culvert--1,0,-1,-1, 0
Deck Dist Width WeirC Skew NumUp NumDn MinLoCord MaxHiCord MaxSubmerge Is_Ogee
10,28,2.6,0, 43, 43, , , 0.95, 0, ,,,
    4258    4518    4738  4797.9  4799.5  4844.8  4873.2  4922.3  4942.3 4953.79
  4953.9 4954.01  4973.8 4976.91 4976.99  4977.1  4982.3  4994.4  4994.7    4997
  4997.3  5001.2  5002.5  5003.1  5007.2  5012.9 5012.99  5013.1  5021.2 5039.59
  5039.7 5039.81  5054.5  5067.7  5101.3  5156.1  5204.5 5204.65  5275.5  5445.5
  5455.5  5585.5  5685.5
   203.7   202.2   199.9  199.88  199.88  199.91  200.04  200.39  200.62  200.75
  201.25  201.25  201.23  201.23  201.23  201.23  201.22  201.21  201.21  201.21
  201.21  201.21   201.2   201.2   201.2  201.19  201.19  201.19  201.19  201.17
  201.17  200.67  200.48  200.29   199.8  199.57  199.71  199.71   199.6   199.9
   200.2   200.5     201
                                                                                
                                  198.15  198.15  198.14  198.13  198.13  198.13
  198.13  198.13  198.12  198.12  198.12  198.11  198.11
                                                                                
                        
    4258    4518    4738  4797.9  4799.5  4844.8  4873.2  4922.3  4942.3 4953.79
  4953.9 4954.01  4973.8 4976.91 4976.99  4977.1  4982.3  4994.4  4994.7    4997
  4997.3  5001.2  5002.5  5003.1  5007.2  5012.9 5012.99  5013.1  5021.2 5039.59
  5039.7 5039.81  5054.5  5067.7  5101.3  5156.1  5204.5 5204.65  5275.5  5445.5
  5455.5  5585.5  5685.5
   203.7   202.2   199.9  199.88  199.88  199.91  200.04  200.39  200.62  200.75
  201.25  201.25  201.23  201.23  201.23  201.23  201.22  201.21  201.21  201.21
  201.21  201.21   201.2   201.2   201.2  201.19  201.19  201.19  201.19  201.17
  201.17  200.67  200.48  200.29   199.8  199.57  199.71  199.71   199.6   199.9
   200.2   200.5     201
                                                                                
                                  198.15  198.15  198.14  198.13  198.13  198.13
  198.13  198.13  198.12  198.12  198.12  198.11  198.11
                                                                                
                        
Pier Skew, UpSta & Num, DnSta & Num=  ,4994.7, 2 ,4994.7, 2 , 0 , 0 , 0 ,,
       1       1
  193.99  199.13
       1       1
  193.99  199.13
BR Coef= 1 , 1 , 1 ,1.25, 0 ,,,0.8,0,2,0,
WSPro=,,,, 1 ,,,, 0 ,,,, 0 ,,,,-1 ,-1 ,-1 , 0 , 0 , 0 , 0 , 0
BC Design=,, 0 ,, 0 ,,,,,,
BC HTab HWMax=203.93

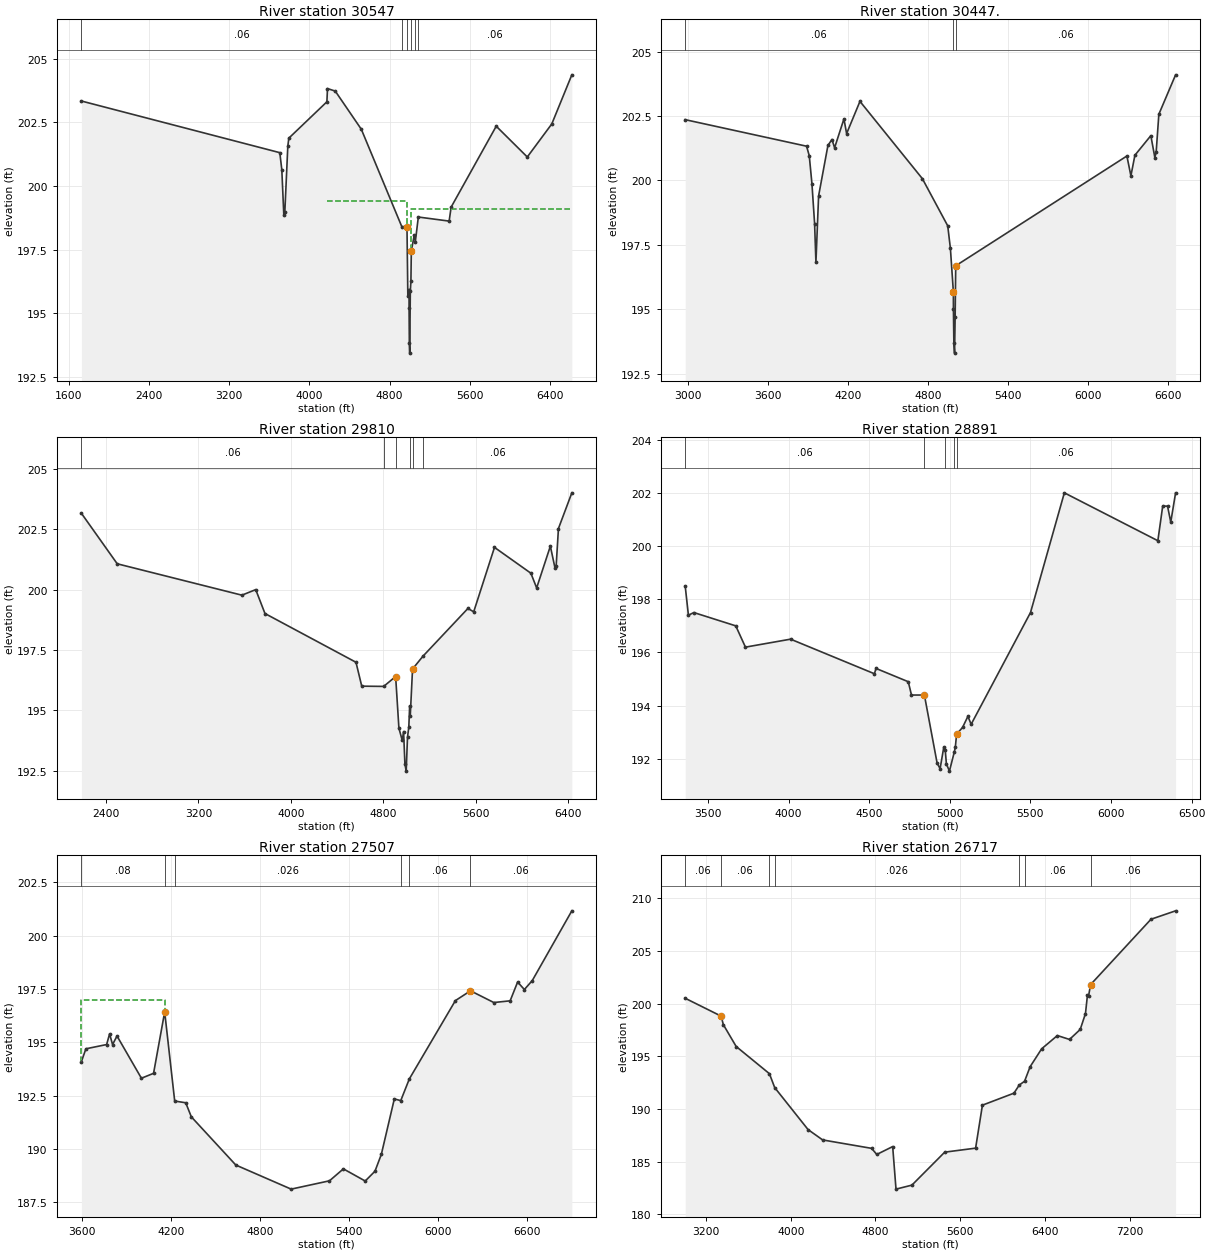
Type RM Length L Ch R = 1 ,30547   ,99,100,111
BEGIN DESCRIPTION:
Downstream Section of Bridge/Culvert/Weir
END DESCRIPTION:
XS GIS Cut Line= 5
      2968222.56     13923167.95      2966016.92     13921919.47
      2966065.95     13921013.71      2966105.69     13919728.71
 2965953.740943513919657.6895844
#Sta/Elev= 30
  1724.4  203.34  3704.4  201.31  3724.4  200.64  3744.4  198.87  3754.4  198.97
  3784.4  201.57  3794.4  201.88  4174.4  203.31  4180.4  203.83    4258  203.73
    4518  202.23  4922.3   198.4  4973.8   198.4  4982.3  195.69  4994.4  195.93
  4994.7  195.22  4997.3  193.81  5001.2  193.43  5007.2  195.88  5013.1  196.26
  5017.1  197.45  5047.1  198.08  5057.1  197.81  5087.1  198.78  5394.6  198.62
  5414.6  199.17  5864.6  202.35  6174.6  201.14  6419.3  202.44  6619.3  204.37
#Mann= 6 ,-1 , 0
  1724.4     .06       0  4922.3     .07       0  4973.8     .06       0
  5017.1     .06       0  5057.1     .08       0  5087.1     .06       0
#XS Ineff= 3 ,-1
    3000  3784.4  201.57    4179 4970.21   199.4 5017.84  6619.3   199.1
Permanent Ineff=
       F       T       F
Bank Sta=4973.8,5017.1
Exp/Cntr=0.5,0.3

Type RM Length L Ch R = 1 ,30447.  ,696.9,637,521.2
BEGIN DESCRIPTION:
Warren Ranch Rd (2) - XS1
END DESCRIPTION:
XS GIS Cut Line= 6
      2967300.93      13922595.4      2966180.31     13921899.05
       2966143.6       13921442.      2966167.05     13920939.45
      2966126.66     13919730.59      2965959.46     13919650.36
#Sta/Elev= 30
  2981.8  202.36  3891.8  201.33  3911.8  200.96  3931.8  199.88  3951.8  198.33
  3961.8  196.82  3981.8   199.4  4051.8  201.36  4081.8  201.59  4101.8  201.27
  4171.8  202.39  4191.8  201.82  4291.8  203.07  4759.7  200.07  4949.7  198.24
  4969.7  197.37    4992  195.68  4992.4  195.03 4995.82  193.69 5000.96   193.3
 5005.35  194.71  5009.7  196.69  6292.8  200.95  6322.8  200.18  6352.8  200.98
  6472.3  201.74  6502.3  200.89  6512.3  201.11  6532.3  202.57  6657.8   204.1
#Mann= 3 ,-1 , 0
  2981.8     .06       0    4992     .07       0  5009.7     .06       0
#XS Ineff= 2 , 0
       0  4051.8  201.36               0
Permanent Ineff=
       F       F
Bank Sta=4992,5009.7
Exp/Cntr=0.3,0.1

Type RM Length L Ch R = 1 ,29810   ,920,919,715.4
BEGIN DESCRIPTION:
INTERP_XS0.7
END DESCRIPTION:
XS GIS Cut Line= 6
      2968277.11     13923080.94      2966895.09     13921145.18
      2966443.72     13920558.87      2966141.26     13920154.04
      2966155.44     13919735.48      2965969.81     13919646.13
#Sta/Elev= 30
  2185.9  203.16  2495.9  201.07  3575.9  199.77  3695.9     200  3775.9  199.01
  4564.4  196.99  4614.4     196  4804.4  195.99    4908   196.4 4936.35  194.26
 4965.29  193.75 4976.72  194.12 4988.34  192.78  4999.4  192.48  5010.8  193.89
    5022   194.3  5029.6  195.19  5034.4  194.75  5054.4  196.71  5144.4  197.24
  5534.3  199.22  5584.3  199.08  5764.3  201.75  6079.6  200.68  6129.6  200.07
  6248.4   201.8  6288.4   200.9  6298.4  200.96  6318.4  202.53  6434.5  204.01
#Mann= 6 ,-1 , 0
  2185.9     .06       0  4804.4     .08       0    4908     .07       0
  5029.6     .08       0  5054.4     .08       0  5144.4     .06       0
Bank Sta=4908,5054.4
Exp/Cntr=0.3,0.1

Type RM Length L Ch R = 1 ,28891   ,1947.5,1384,1034.6
BEGIN DESCRIPTION:
Cross Section K160-00-00-X18
END DESCRIPTION:
XS GIS Cut Line= 4
      2968337.64      13921723.9      2968335.13     13921670.39
      2966949.98     13920107.65      2966140.48      13919714.3
#Sta/Elev= 30
  3358.5   198.5  3378.5   197.4  3412.2   197.5  3672.2     197  3732.2   196.2
  4012.2   196.5  4532.2   195.2  4542.2   195.4  4742.2   194.9  4762.2   194.4
  4842.2   194.4  4920.9  191.85  4939.6  191.63  4962.5  192.44  4971.7  192.32
  4978.8  191.81  4997.6  191.54  5028.2  192.27    5034  192.43  5042.1  192.93
  5078.8  193.18  5112.2   193.6  5132.2   193.3  5500.4   197.5  5710.4     202
  6290.4   200.2  6320.4   201.5  6350.4   201.5  6370.4   200.9  6400.4     202
#Mann= 5 ,-1 , 0
  3358.5     .06       0  4842.2     .07       0  4971.7     .06       0
  5028.2     .07       0  5042.1     .06       0
Bank Sta=4842.2,5042.1
Exp/Cntr=0.3,0.1

Type RM Length L Ch R = 1 ,27507   ,646.6,790,826
BEGIN DESCRIPTION:
Cross Section K160-00-00-X17
Left side spills into K157-00 VRR
END DESCRIPTION:
XS GIS Cut Line= 4
      2969471.95     13919595.05      2968950.57     13919347.18
      2966815.53     13919488.38 2966239.955804713919352.1464433
#Sta/Elev= 30
  3595.5   194.1  3625.5   194.7  3765.5   194.9  3785.5   195.4  3805.5   194.9
  3835.5   195.3  4000.1  193.32  4082.1  193.55  4157.1  196.43  4224.7  192.25
  4299.1  192.17  4336.9  191.51    4637  189.25  5010.4  188.12  5268.9  188.51
  5362.7  189.07    5510   188.5  5575.9  188.96  5618.8  189.75  5706.4  192.35
  5749.7  192.27  5807.8  193.29  6118.4  196.96  6220.3  197.42  6377.6  196.87
  6487.8  196.95  6538.1  197.83  6583.7  197.48  6637.1   197.9    6904  201.17
#Mann= 6 ,-1 , 0
  3595.5     .08       0  4157.1     .08       0  4224.7    .026       0
  5749.7     .08       0  5807.8     .06       0  6220.3     .06       0
#XS Ineff= 2 , 0
         4157.01  197.01
Permanent Ineff=
       F       F
Bank Sta=4157.1,6220.3
Exp/Cntr=0.3,0.1

Type RM Length L Ch R = 1 ,26717   ,1489.5,1406,1373.4
BEGIN DESCRIPTION:
Cross Section K160-00-00-X16
END DESCRIPTION:
XS GIS Cut Line= 4
      2969617.78     13918272.13      2969262.74      13918795.5
      2966701.41     13918621.93      2965274.03      13918501.3
#Sta/Elev= 30
  3002.6   200.5  3342.6   198.8  3362.6     198  3484.3  195.92  3798.1  193.34
    3848  192.02  4163.5  188.03  4301.3  187.05  4763.9  186.25    4812  185.67
  4962.4  186.42  4993.8  182.38  5144.1  182.76    5454  185.89  5745.7  186.27
  5810.1  190.35    6108  191.49  6157.9  192.26  6208.2  192.62  6260.6     194
  6369.4   195.7    6518  196.96  6632.8  196.59  6733.9  197.54  6783.5  199.05
  6802.2   200.8  6812.2   200.7  6832.2   201.8  7402.2     208  7634.7   208.8
#Mann= 7 ,-1 , 0
  3002.6     .06       0  3342.6     .06       0  3798.1     .08       0
    3848    .026       0  6157.9     .08       0  6208.2     .06       0
  6832.2     .06       0
Bank Sta=3342.6,6832.2
Exp/Cntr=0.3,0.1

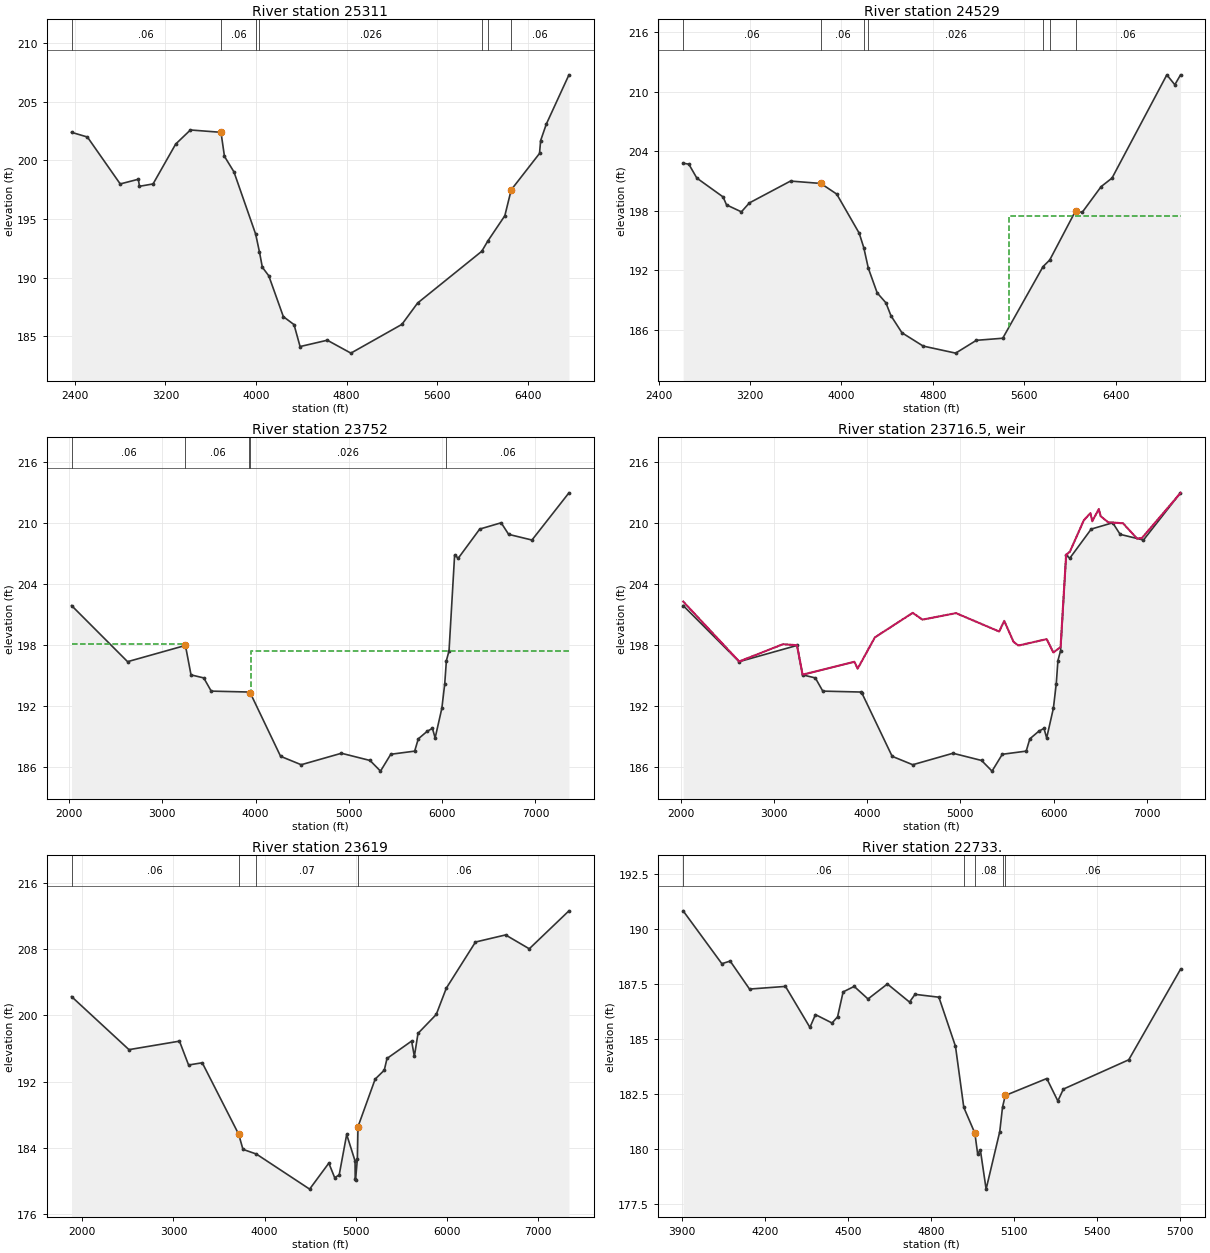
Type RM Length L Ch R = 1 ,25311   ,634.6,782,789.1
BEGIN DESCRIPTION:
Cross Section K160-00-00-X15
END DESCRIPTION:
XS GIS Cut Line= 4
      2970294.87      13917438.8      2968659.67     13917314.52
      2966576.51     13917355.03 2965927.802433413917187.4173884
#Sta/Elev= 30
  2370.8   202.4  2510.8     202  2800.8     198  2960.8   198.4  2970.8   197.8
  3090.8     198  3290.8   201.4  3420.8   202.6  3690.8   202.4  3721.6  200.35
  3805.2  199.03  3997.2  193.72  4030.9  192.19  4056.1   190.9    4113  190.17
  4241.6  186.69    4336  186.01  4389.4  184.14  4629.8  184.68  4838.3  183.58
  5288.8  186.03  5427.5  187.85  5994.2  192.26  6046.6  193.12  6197.9  195.29
  6254.3   197.5  6504.3   200.6  6514.3   201.7  6564.3   203.1  6764.3   207.3
#Mann= 7 ,-1 , 0
  2370.8     .06       0  3690.8     .06       0  3997.2     .08       0
  4030.9    .026       0  5994.2     .08       0  6046.6     .06       0
  6254.3     .06       0
Bank Sta=3690.8,6254.3
Exp/Cntr=0.3,0.1

Type RM Length L Ch R = 1 ,24529   ,1028.8,777,382.5
BEGIN DESCRIPTION:
Cross Section K160-00-00-X14
END DESCRIPTION:
XS GIS Cut Line= 4
      2970305.28     13917355.46      2969202.74     13916854.38
      2966720.37     13916460.73 2966107.226452413916605.8824117
#Sta/Elev= 30
  2613.9   202.8  2663.9   202.7  2733.9   201.3  2963.9   199.4  2993.9   198.6
  3123.9   197.9  3193.9   198.8  3553.9     201  3819.3  200.76  3958.4  199.69
  4155.3  195.75  4195.7  194.28    4235  192.23  4312.6  189.74    4389  188.74
  4433.2  187.44  4529.6  185.72  4715.3  184.38  4999.7  183.67  5181.1  184.96
  5411.8  185.17    5765  192.39  5823.2  193.05  6050.5  198.02  6106.9  197.84
  6273.1  200.44  6368.4   201.3  6848.4   211.7  6918.4   210.7  6968.4   211.7
#Mann= 7 ,-1 , 0
  2613.9     .06       0  3819.3     .06       0  4195.7     .08       0
    4235    .026       0    5765     .08       0  5823.2     .06       0
  6050.5     .06       0
#XS Ineff= 2 , 0
                         5464.53           197.5
Permanent Ineff=
       F       F
Bank Sta=3819.3,6050.5
Exp/Cntr=0.7,0.5

Type RM Length L Ch R = 1 ,23752   ,134.5,133,132
BEGIN DESCRIPTION:
Upstream Section of Bridge/Culvert/Weir
END DESCRIPTION:
XS GIS Cut Line= 5
      2970406.62      13916886.2      2969105.15     13916327.02
      2967745.14     13916209.17      2966645.39     13916386.71
      2965250.37     13916729.95
#Sta/Elev= 30
  2027.4  201.91  2628.3  196.38  3248.3  197.98  3308.2  195.08  3444.8  194.78
  3524.8  193.48  3933.4  193.39  3941.4  193.34  4268.4  187.06  4489.3  186.23
  4920.6  187.36  5227.2  186.65  5339.4   185.6  5449.4  187.26  5705.8  187.57
  5744.5  188.78  5840.8  189.53  5896.2  189.81  5925.1  188.87  5997.1  191.79
  6028.1  194.21  6045.7  196.48  6074.1  197.45  6133.9  206.88    6173  206.57
    6403  209.44    6633  210.06    6713  208.92    6963  208.36  7359.6  213.01
#Mann= 5 ,-1 , 0
  2027.4     .06       0  3248.3     .06       0  3933.4    .026       0
  3941.4    .026       0  6045.7     .06       0
#XS Ineff= 2 , 0
       0 3250.86  198.12 3951.56       0  197.46
Permanent Ineff=
       F       F
Bank Sta=3248.3,3941.4
Exp/Cntr=0.7,0.5

Type RM Length L Ch R = 5 ,23716.5 ,,,
BEGIN DESCRIPTION:
WARREN LAKE DAM
Structure ID: K160-00-00-S02
This lake has 2 ft. diameter riser that keeps the lake's W.S. elevation at or below 192.27 per survey.  Storages need to be adjusted to take this into account.
END DESCRIPTION:
IW Pilot Flow=0
#Inline Weir SE= 30
  2028.3   202.3  2628.3   196.4  3098.3   198.1  3248.3     198  3308.2   195.1
  3863.5  196.37  3898.5  195.69  4083.1  198.77  4488.8  201.19  4593.1  200.52
  4953.2  201.16  5416.2  199.35  5469.7   200.4  5569.6  198.34  5622.3  197.97
  5925.5   198.6  5997.1  197.28  6074.1  197.82  6133.9  206.91  6173.9  207.21
  6323.9  210.31  6393.9  211.01  6413.9  210.21  6483.9  211.41  6503.9  210.71
  6583.9  210.11  6743.9  210.01  6893.9  208.51  6946.7  208.56  7360.5     213
IW Dist,WD,Coef,Skew,MaxSub,Min_El,Is_Ogee,SpillHt,DesHd
28,15,3,0,0.95,, 0 ,,,0,0,

Type RM Length L Ch R = 1 ,23619   ,887,886,695.7
BEGIN DESCRIPTION:
Cross Section FIELD_DS
Located At: WARREN LAKE DAM;Spillway shown on right
END DESCRIPTION:
XS GIS Cut Line= 6
       2970468.1     13916866.84      2969426.44     13916304.34
      2968266.86     13916067.75      2967673.48     13916044.47
      2967359.07     13916188.25       2965280.6       13916721.
#Sta/Elev= 30
  1882.1  202.29  2512.1  195.86  3065.9  196.89  3165.9     194  3315.9  194.27
    3715  185.62  3762.4  183.78  3909.6  183.21  4493.7  178.96  4704.2  182.11
  4768.3  180.35  4817.9  180.68  4900.1  185.58  4991.9  182.37  4993.5  180.18
  4997.1  180.03  5017.6  182.67  5024.1  186.52  5212.4  192.29  5312.4  193.37
  5342.4  194.79  5612.4   196.9  5642.4  195.04  5682.4  197.83  5882.4  200.12
  5992.9  203.31  6312.9   208.9  6642.9  209.76  6902.9  208.08  7338.1  212.68
#Mann= 4 ,-1 , 0
  1882.1     .06       0    3715     .06       0  3909.6     .07       0
  5024.1     .06       0
Bank Sta=3715,5024.1
Exp/Cntr=0.7,0.5

Type RM Length L Ch R = 1 ,22733.  ,201.7,195,153.2
BEGIN DESCRIPTION:
Warren Lake Dam - XS1
END DESCRIPTION:
XS GIS Cut Line= 5
       2969142.5      13916091.7      2968732.52     13915968.28
       2968302.7     13915741.01      2967839.94     13915561.51
      2967454.58     13915523.63
#Sta/Elev= 30
  3904.8  190.82  4044.8  188.42  4074.8  188.54  4144.8  187.27  4274.8  187.39
  4363.1  185.53  4383.1  186.11  4443.1  185.73  4463.1  186.01  4483.1  187.14
  4523.1  187.39  4573.1  186.82  4643.1   187.5  4723.1  186.68  4743.1  187.03
  4829.3   186.9  4889.3  184.67  4919.3   181.9  4959.3  180.73  4969.3   179.8
  4979.3  179.96    5000  178.19  5049.3   180.8  5059.3  181.91  5069.3  182.44
  5219.3  183.21  5259.3  182.19  5279.3  182.73  5515.6  184.06  5702.8  188.17
#Mann= 5 ,-1 , 0
  3904.8     .06       0  4919.3     .08       0  4959.3     .08       0
  5059.3     .06       0  5069.3     .06       0
Bank Sta=4959.3,5069.3
Exp/Cntr=0.3,0.1