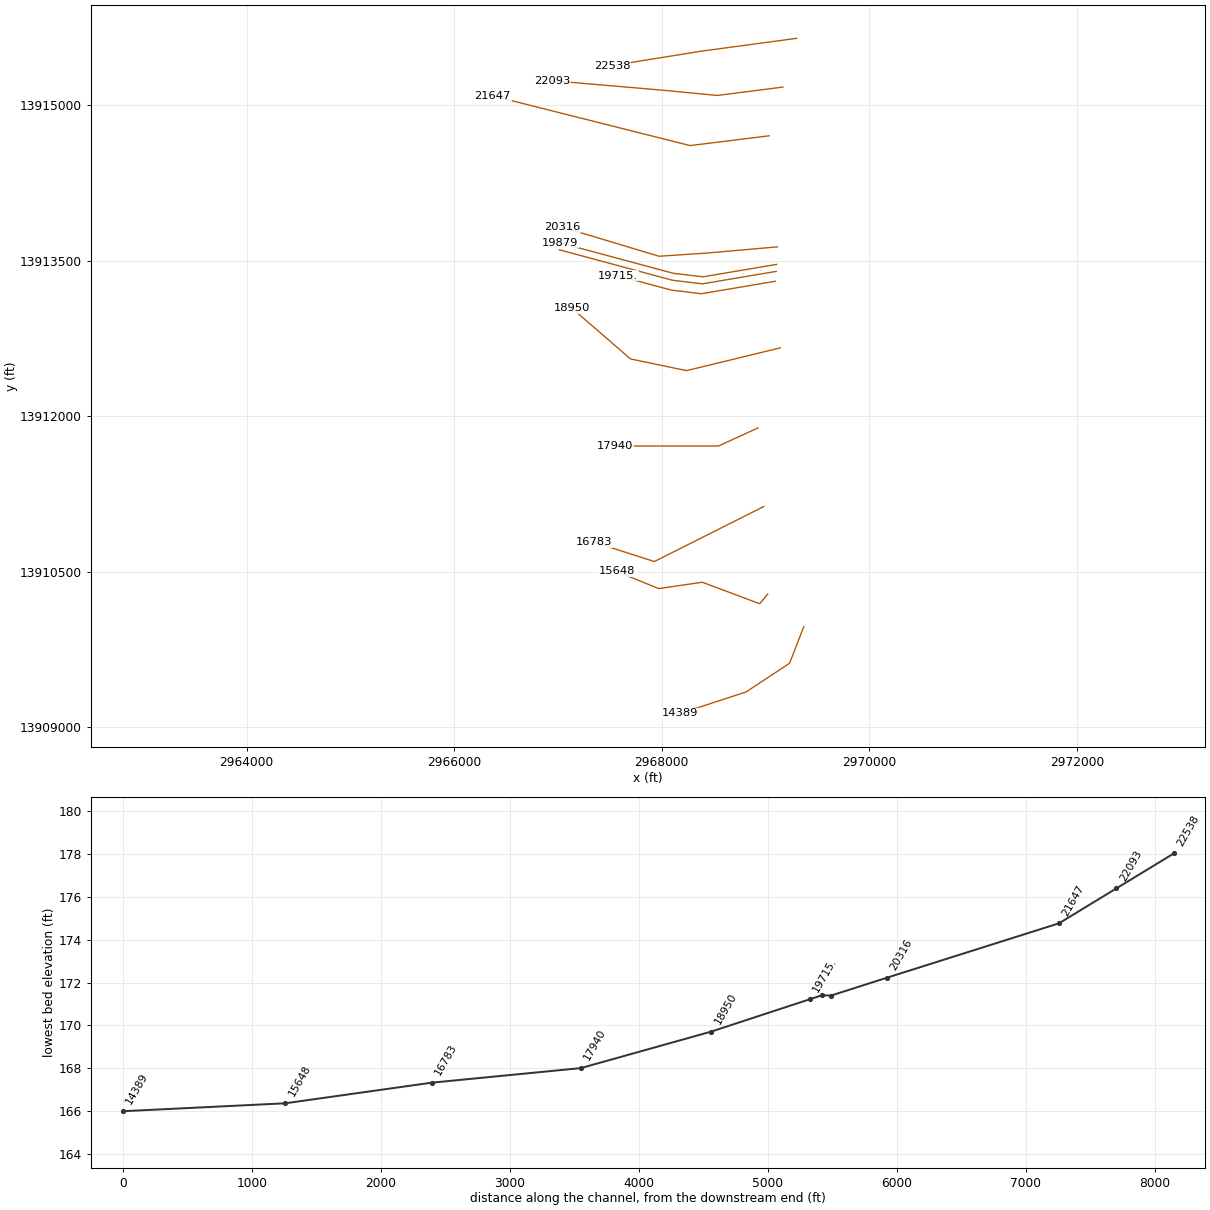
HEC-RAS study K160-00-00.prj: K160-00-00

--- K160-00-00.g02 (geometry) --- (continued)

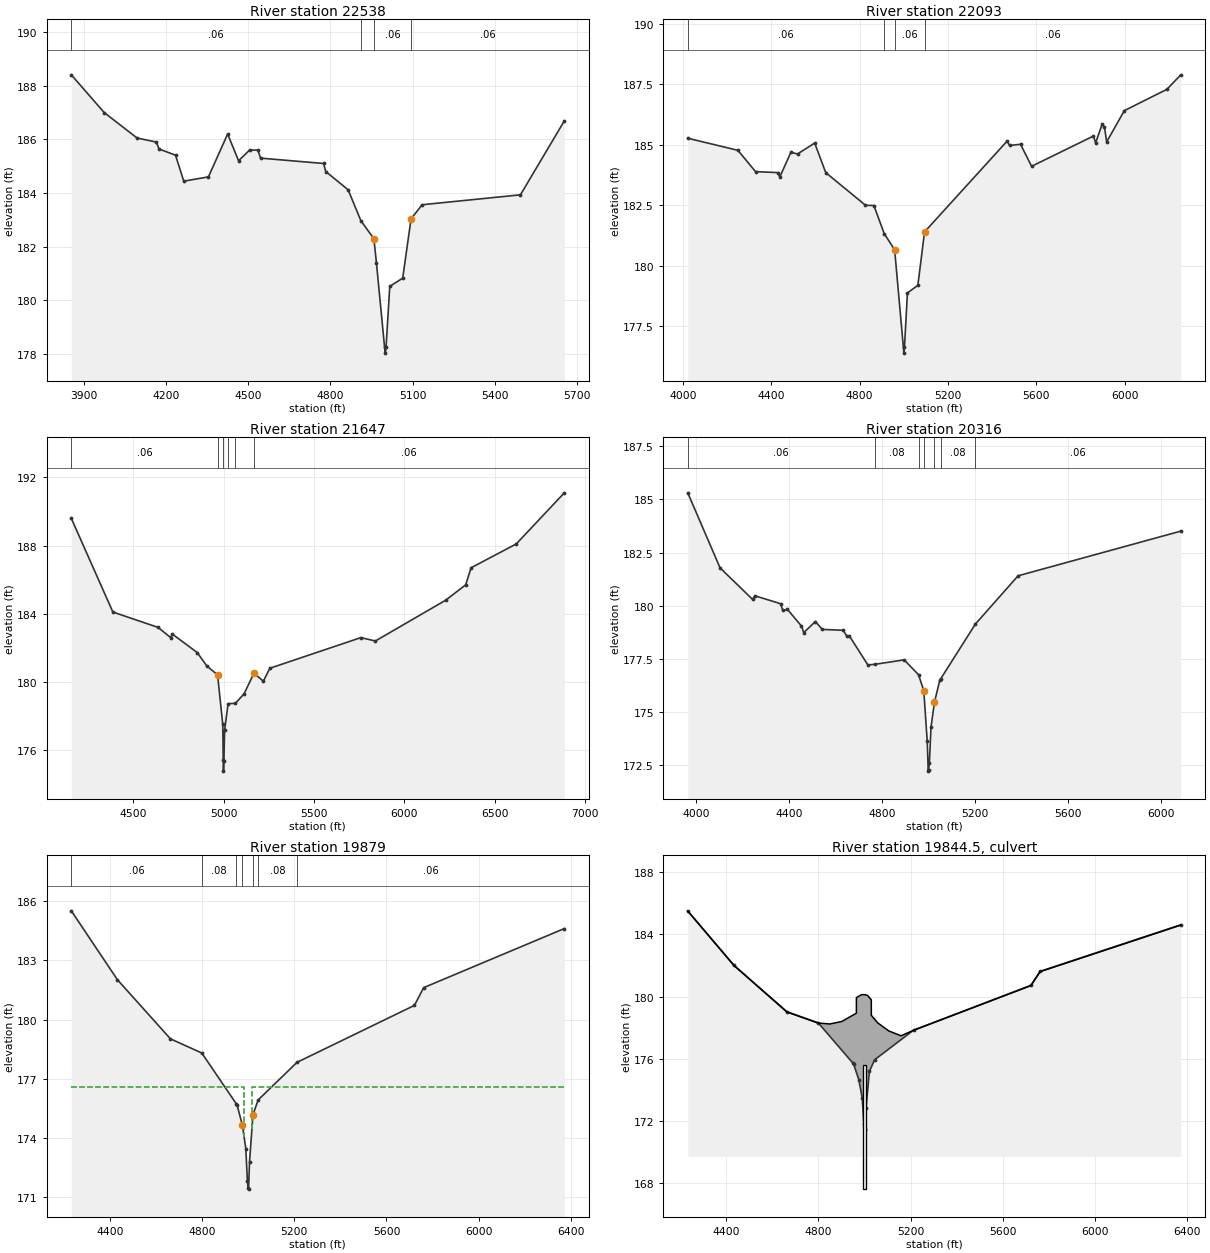
Type RM Length L Ch R = 1 ,22538   ,447,445.5,323.3
BEGIN DESCRIPTION:
Cross Section K160-00-00-X13
END DESCRIPTION:
XS GIS Cut Line= 3
 2969299.337640613915643.3892332      2968379.96     13915519.51
  2967520.97384913915381.2524821
#Sta/Elev= 28
  3855.1  188.41  3975.1     187  4095.1  186.05  4165.1   185.9  4175.1  185.64
  4235.1  185.41  4265.1  184.44  4355.1   184.6  4425.1   186.2  4465.1   185.2
  4505.1   185.6  4535.1   185.6  4545.1   185.3  4775.1   185.1  4782.8   184.8
  4864.4  184.12  4911.1  182.96  4958.4  182.29  4967.8  181.38  4997.2  178.26
  5000.3  178.02  5002.9  178.26  5016.3  180.51  5063.5  180.82  5093.9  183.03
  5134.2  183.56  5492.8  183.93  5652.8  186.69
#Mann= 4 ,-1 , 0
  3855.1     .06       0  4911.1     .08       0  4958.4     .06       0
  5093.9     .06       0
Bank Sta=4958.4,5093.9
Exp/Cntr=0.3,0.1

Type RM Length L Ch R = 1 ,22093   ,504.7,445.5,444
BEGIN DESCRIPTION:
Cross Section K160-00-00-X12A
END DESCRIPTION:
XS GIS Cut Line= 5
       2969167.1      13915173.4      2968534.63     13915092.58
      2968263.75     13915118.68      2968016.04     13915142.55
      2966946.26     13915234.73
#Sta/Elev= 30
 4021.63  185.27  4248.6  184.77  4328.6  183.89  4428.6  183.85  4438.6  183.67
  4488.6  184.69  4518.6  184.62  4596.4  185.07  4646.4  183.85  4826.4   182.5
  4864.4  182.49  4911.1  181.33  4958.4  180.66  5000.3  176.39  5002.9  176.63
  5016.3  178.88  5063.5  179.19  5093.9   181.4  5468.5  185.16  5478.5  184.97
  5528.5  185.02  5578.5  184.11  5858.5  185.36  5868.5  185.08  5898.5  185.86
  5908.5  185.73  5918.5  185.12  5998.5  186.41  6191.1  187.29 6253.97  187.89
#Mann= 4 ,-1 , 0
 4021.63     .06       0  4911.1     .08       0  4958.4     .06       0
  5093.9     .06       0
Bank Sta=4958.4,5093.9
Exp/Cntr=0.3,0.1

Type RM Length L Ch R = 1 ,21647   ,1330,1331,1332
BEGIN DESCRIPTION:
Cross Section K160-00-00-X12
END DESCRIPTION:
XS GIS Cut Line= 4
 2969035.058086413914703.5767612      2968271.96     13914609.42
       2967948.2     13914690.99      2966371.55      13915088.2
#Sta/Elev= 26
  4157.3   189.6  4387.3   184.1  4637.3   183.2  4707.3   182.6  4717.3   182.8
  4854.5  181.72  4906.8  180.94  4966.8  180.41  4995.6   177.5    4998  175.42
  4999.6  174.76  5001.9  175.37  5005.7  177.16    5025  178.72  5065.4  178.74
  5113.6   179.3  5168.1  180.51  5220.1  180.04  5256.2   180.8  5760.1   182.6
  5840.1   182.4  6230.1   184.8  6340.1   185.7  6370.1   186.7  6620.1   188.1
    6886   191.1
#Mann= 6 ,-1 , 0
  4157.3     .06       0  4966.8     .08       0  4995.6     .06       0
    5025     .08       0  5065.4     .06       0  5168.1     .06       0
Bank Sta=4966.8,5168.1
Exp/Cntr=0.3,0.1

Type RM Length L Ch R = 1 ,20316   ,436,437,438
BEGIN DESCRIPTION:
INTERP_XS0.7.1
END DESCRIPTION:
XS GIS Cut Line= 4
      2969114.66      13913632.7       2968438.1      13913573.3
      2967973.29      13913542.3      2967038.51      13913823.8
#Sta/Elev= 30
  3965.3  185.31  4104.4  181.78  4244.4   180.3  4254.4  180.47  4364.4   180.1
  4374.4  179.78  4394.4  179.83  4454.4  179.05  4464.4  178.74  4514.4  179.26
  4544.4  178.89  4634.4  178.85  4650.3  178.56  4660.3  178.59  4740.3  177.22
  4770.3  177.25  4896.5  177.46  4958.3  176.76  4980.8  176.01  4995.7  173.63
    5000  172.23  5001.4  172.29  5004.9  172.62  5011.9  174.29  5026.7  175.47
  5049.7   176.5  5053.7  176.57  5202.7  179.14  5386.5  181.41  6086.5  183.51
#Mann= 7 ,-1 , 0
  3965.3     .06       0  4770.3     .08       0  4958.3     .07       0
  4980.8     .07       0  5026.7     .07       0  5053.7     .08       0
  5202.7     .06       0
Bank Sta=4980.8,5026.7
Exp/Cntr=0.5,0.3

Type RM Length L Ch R = 1 ,19879   ,67,68,116.9
BEGIN DESCRIPTION:
Upstream Section of Bridge/Culvert/Weir
END DESCRIPTION:
XS GIS Cut Line= 4
 2969106.155998413913463.8207306      2968396.21     13913343.86
      2968109.47      13913378.1 2967018.791610113913671.8302638
#Sta/Elev= 18
  4233.2  185.52  4433.2  182.02  4663.2  179.02  4799.2   178.3  4948.2  175.73
  4952.2  175.66  4975.2  174.63    4990  173.45    4997  171.78  5000.5  171.45
  5001.9  171.39  5006.2  172.79  5021.1  175.17  5043.6  175.92  5212.4  177.83
 5721.53  180.72  5761.5  181.62  6371.5  184.62
#Mann= 7 ,-1 , 0
  4233.2     .06       0  4799.2     .08       0  4948.2     .07       0
  4975.2     .07       0  5021.1     .07       0  5043.6     .08       0
  5212.4     .06       0
#XS Ineff= 2 , 0
       0 4982.43   176.6  5016.4       0   176.6
Permanent Ineff=
       F       F
Bank Sta=4975.2,5021.1
Exp/Cntr=0.5,0.3

Type RM Length L Ch R = 2 ,19844.5 ,,,
BEGIN DESCRIPTION:
WARREN RANCH RD.(1); Jack Road in Fema model 11/5/2 VRR
Structure ID: K160-00-00-S1; Lots of debris in channel 11/6/2 VRR
END DESCRIPTION:
Bridge Culvert--1,0,-1,-1, 0
Deck Dist Width WeirC Skew NumUp NumDn MinLoCord MaxHiCord MaxSubmerge Is_Ogee
10,49,3,0, 37, 37, , , 0.95, 0, ,,,
  4233.2  4433.2  4663.2  4783.4  4799.2  4849.5  4901.2  4948.2  4952.2 4964.59
  4964.7 4964.81  4975.2  4987.6    4990    4997  4998.3  5000.5  5001.5  5001.9
    5003  5006.2  5008.9  5013.7  5021.1 5029.19  5029.3 5029.41  5043.6  5057.2
  5105.4  5157.9  5212.4  5721.4 5721.53  5761.5  6371.5
   185.5     182     179  178.37  178.29  178.23  178.39  178.79  178.82  178.93
  179.93  179.93  180.02  180.12  180.12  180.12  180.12  180.12  180.12  180.12
  180.11   180.1  180.08  180.06  179.93  179.79  179.79  178.79  178.54   178.3
  177.78  177.47  177.82   180.7   180.7   181.6   184.6
                                                                                
                                                                                
                                                                                
                                                        
  4233.2  4433.2  4663.2  4783.4  4799.2  4849.5  4901.2  4948.2  4952.2 4964.59
  4964.7 4964.81  4975.2  4987.6    4990    4997  4998.3  5000.5  5001.5  5001.9
    5003  5006.2  5008.9  5013.7  5021.1 5029.19  5029.3 5029.41  5043.6  5057.2
  5105.4  5157.9  5212.4  5721.4 5721.53  5761.5  6371.5
   185.5     182     179  178.37  178.29  178.23  178.39  178.79  178.82  178.93
  179.93  179.93  180.02  180.12  180.12  180.12  180.12  180.12  180.12  180.12
  180.11   180.1  180.08  180.06  179.93  179.79  179.79  178.79  178.54   178.3
  177.78  177.47  177.82   180.7   180.7   181.6   184.6
                                                                                
                                                                                
                                                                                
                                                        
BR Coef= 1 , 1 , 1 ,1.25, 0 ,,,0.8,0,2,0,
WSPro=,,,, 1 ,,,, 0 ,,,, 0 ,,,,-1 ,-1 ,-1 , 0 , 0 , 0 , 0 , 0
Culvert=2,8,14,49,0.015,0.5,1,8,2,167.59,4999.4,167.47,4999.4,Culvert #1  , 0 ,10
Culvert Bottom n=0.02
BC Design=,, 0 ,, 0 ,,,,,,
BC HTab HWMax=185.52

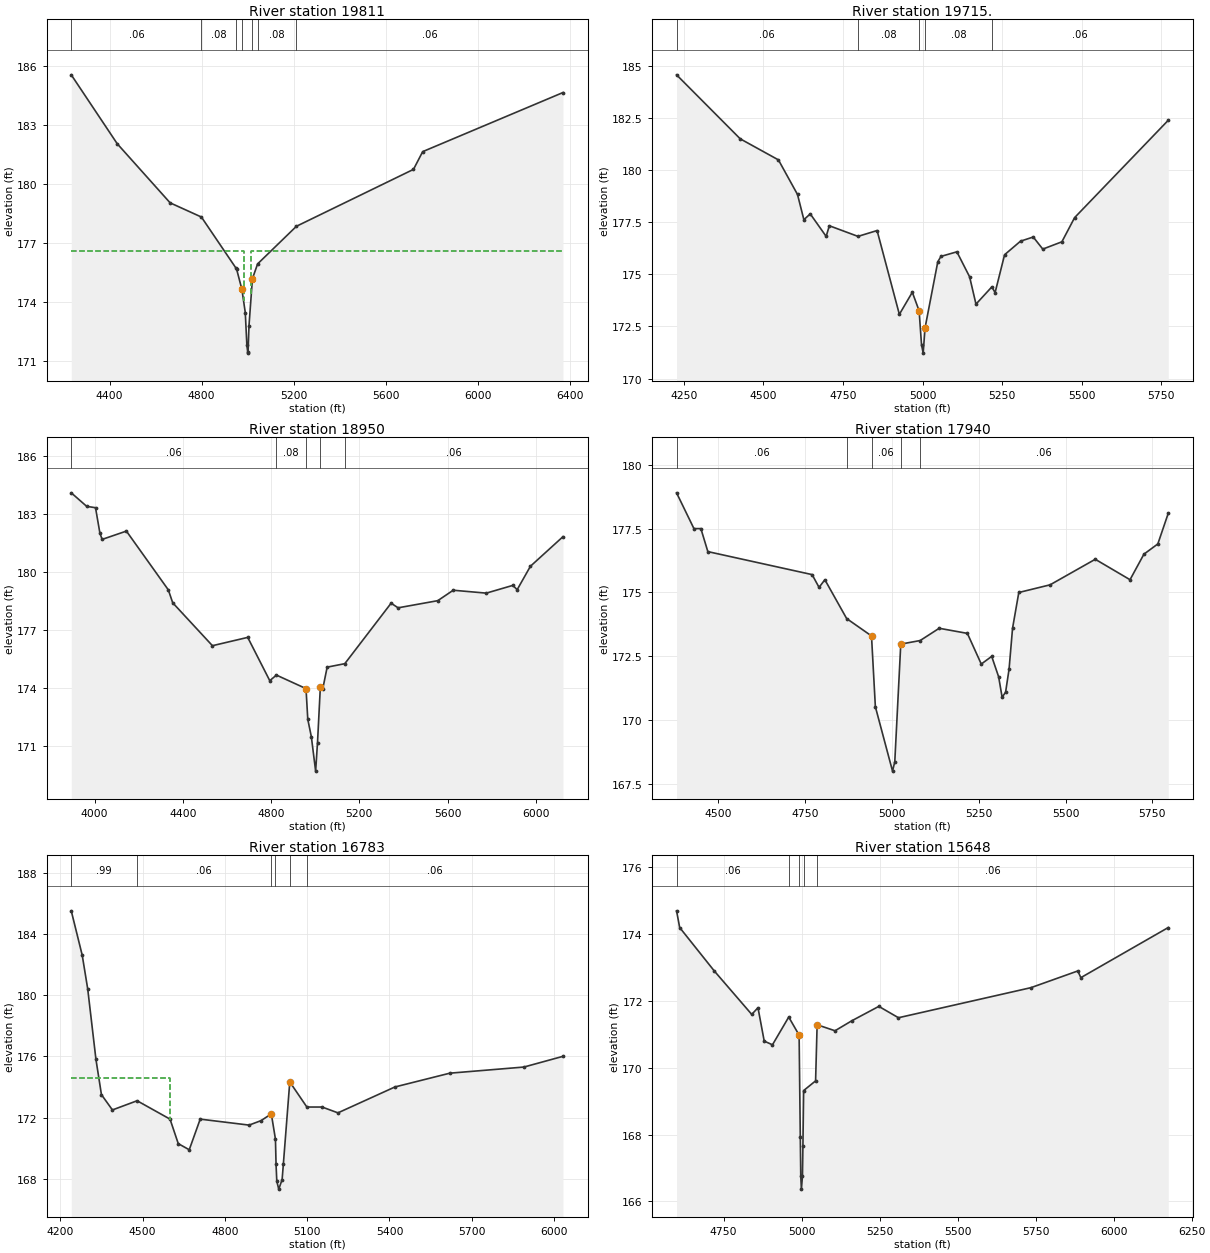
Type RM Length L Ch R = 1 ,19811   ,100.1,96,95
BEGIN DESCRIPTION:
Downstream Section of Bridge/Culvert/Weir
END DESCRIPTION:
XS GIS Cut Line= 4
 2969102.116002213913396.3407079      2968391.46     13913276.26
      2968103.64     13913310.63 2967012.621749613913604.4507818
#Sta/Elev= 18
  4233.2  185.54  4433.2  182.04  4663.2  179.04  4799.2  178.32  4948.2  175.75
  4952.2  175.68  4975.2  174.65    4990  173.47    4997   171.8  5000.5  171.47
  5001.9  171.41  5006.2  172.81  5021.1  175.19  5043.6  175.94  5212.4  177.85
 5721.53  180.74  5761.5  181.64  6371.5  184.64
#Mann= 7 ,-1 , 0
  4233.2     .06       0  4799.2     .08       0  4948.2     .07       0
  4975.2     .07       0  5021.1     .07       0  5043.6     .08       0
  5212.4     .06       0
#XS Ineff= 2 , 0
       0 4982.44   176.6 5016.33       0   176.6
Permanent Ineff=
       F       F
Bank Sta=4975.2,5021.1
Exp/Cntr=0.5,0.3

Type RM Length L Ch R = 1 ,19715.  ,801.1,765,732.2
BEGIN DESCRIPTION:
Warren Ranch Rd (1) - XS1
END DESCRIPTION:
XS GIS Cut Line= 4
      2969092.88       13913301.      2968382.23     13913180.93
      2968094.41      13913215.3      2967578.58     13913354.22
#Sta/Elev= 30
  4227.1  184.57  4427.1   181.5  4547.1  180.49  4607.1  178.83  4627.1  177.62
  4647.1   177.9  4697.1  176.82  4707.1  177.33  4797.1  176.82  4857.1   177.1
  4927.1  173.08  4967.8  174.14 4989.18  173.25 4996.68  171.63 5001.92  171.22
  5007.8  172.43  5047.8   175.6  5057.8  175.86  5107.8  176.08  5147.8  174.88
  5167.8  173.57  5217.8   174.4  5227.8  174.12  5257.7  175.94  5307.7  176.59
  5347.7  176.79  5377.7  176.21  5437.7  176.56  5477.7  177.72  5771.9  182.39
#Mann= 5 ,-1 , 0
  4227.1     .06       0  4797.1     .08       0 4989.18     .07       0
  5007.8     .08       0  5217.8     .06       0
Bank Sta=4989.18,5007.8
Exp/Cntr=0.3,0.1

Type RM Length L Ch R = 1 ,18950   ,794.2,1010,1011
BEGIN DESCRIPTION:
INTERP_XS0.6
END DESCRIPTION:
XS GIS Cut Line= 4
      2969141.86     13912659.05      2968238.04     13912439.37
      2967698.26     13912552.35      2967133.38     13913041.91
#Sta/Elev= 30
  3894.2  184.11  3964.2  183.41  4004.2  183.34  4024.2  182.02  4034.2   181.7
  4144.2  182.13  4334.2  179.09  4354.2  178.42  4534.2   176.2  4694.2  176.63
  4794.2  174.39  4824.3  174.68  4958.5  173.98  4966.5  172.39 4982.67  171.49
  5002.1  169.71 5010.61  171.19 5023.55  174.08  5034.3  173.96  5054.3  175.09
  5134.3  175.27  5344.3   178.4  5375.8  178.16  5555.8  178.53  5625.8  179.07
  5775.8  178.92  5895.8  179.32  5915.8   179.1  5975.8  180.31  6123.3  181.84
#Mann= 5 ,-1 , 0
  3894.2     .06       0  4824.3     .08       0  4958.5     .07       0
 5023.55     .08       0  5134.3     .06       0
Bank Sta=4958.5,5023.55
Exp/Cntr=0.3,0.1

Type RM Length L Ch R = 1 ,17940   ,1023.6,1157,1158
BEGIN DESCRIPTION:
Cross Section K160-00-00-X11
END DESCRIPTION:
XS GIS Cut Line= 4
 2968925.846109113911886.6308689      2968547.17     13911712.82
      2967989.08     13911712.82 2967549.1299023     13911712.82
#Sta/Elev= 30
  4380.9   178.9  4430.9   177.5  4450.9   177.5  4470.9   176.6  4770.9   175.7
  4790.9   175.2  4807.6   175.5  4870.3  173.98  4941.8   173.3  4952.9  170.53
  5002.3  168.01  5008.8  168.38    5026  172.98  5081.8  173.12  5136.6   173.6
  5217.6   173.4  5257.6   172.2  5287.6   172.5  5307.6   171.7  5317.6   170.9
  5327.6   171.1  5337.6     172  5347.6   173.6  5365.6     175  5455.6   175.3
  5585.6   176.3  5685.6   175.5  5725.6   176.5  5765.6   176.9  5795.6   178.1
#Mann= 5 ,-1 , 0
  4380.9     .06       0  4870.3     .08       0  4941.8     .06       0
    5026     .08       0  5081.8     .06       0
Bank Sta=4941.8,5026
Exp/Cntr=0.3,0.1

Type RM Length L Ch R = 1 ,16783   ,1136,1135,526.7
BEGIN DESCRIPTION:
Cross Section K160-00-00-X10
END DESCRIPTION:
XS GIS Cut Line= 3
 2968982.362322413911128.9518655      2967928.68     13910598.67
      2967345.57     13910785.74
#Sta/Elev= 28
  4240.3   185.5  4280.3   182.6  4300.3   180.4  4330.3   175.8  4350.3   173.5
  4390.3   172.5  4480.3   173.1  4600.3   171.9  4630.3   170.3  4670.3   169.9
  4710.3   171.9  4888.4  171.51  4931.7   171.8  4969.5  172.24  4984.5  170.59
  4986.7  168.95  4989.4  167.85  4996.5  167.33  5008.8  167.95  5013.3  168.96
  5036.7  174.33    5099  172.69  5154.5  172.69  5212.3  172.31  5419.9     174
  5619.9   174.9  5889.9   175.3  6032.3     176
#Mann= 6 ,-1 , 0
  4240.3     .99       0  4480.3     .06       0  4969.5     .08       0
  4984.5     .06       0  5036.7     .08       0    5099     .06       0
#XS Ineff= 2 , 0
         4601.21  174.56
Permanent Ineff=
       F       F
Bank Sta=4969.5,5036.7
Exp/Cntr=0.3,0.1

Type RM Length L Ch R = 1 ,15648   ,967.8,1259,1260
BEGIN DESCRIPTION:
Cross Section K160-00-00-X9
END DESCRIPTION:
XS GIS Cut Line= 5
   2969020.4630713910284.7799334      2968943.17     13910191.85
      2968390.66     13910399.04      2967970.57     13910337.82
 2967563.196739213910504.0990352
#Sta/Elev= 25
  4599.3   174.7  4609.3   174.2  4720.2   172.9  4840.2   171.6  4860.2   171.8
  4880.2   170.8  4906.6  170.69  4958.7  171.52    4992  170.98  4995.8  167.92
  4997.3  166.76  4999.3  166.37  5002.7  166.76  5004.2  167.66  5006.5  169.32
  5044.8  169.61  5049.7  171.29    5107  171.11    5161  171.41  5247.4  171.84
  5310.3   171.5  5734.8   172.4  5884.8   172.9  5894.8   172.7  6174.8   174.2
#Mann= 5 ,-1 , 0
  4599.3     .06       0  4958.7     .08       0    4992     .06       0
  5006.5     .08       0  5049.7     .06       0
Bank Sta=4992,5049.7
Exp/Cntr=0.3,0.1

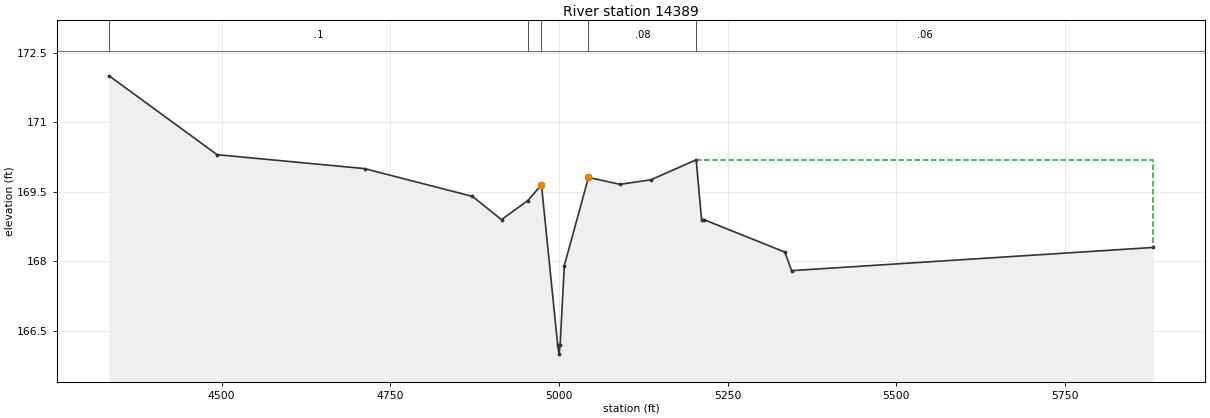
Type RM Length L Ch R = 1 ,14389   ,654.7,1217,1218
BEGIN DESCRIPTION:
Cross Section K160-00-00-X8
Right overbank spills into K160-01-00.
END DESCRIPTION:
XS GIS Cut Line= 5
 2969368.205319113909971.3085789      2969231.64      13909618.3
      2969065.18     13909508.39      2968811.98     13909341.22
       2968178.9      13909134.7
#Sta/Elev= 20
  4333.4     172  4493.4   170.3  4711.9     170  4871.9   169.4  4914.9   168.9
  4953.8  169.31  4974.1  169.65  4998.2  166.19  5000.2     166  5001.8   166.2
    5008  167.91  5043.8  169.81  5090.4  169.66  5136.7  169.76  5203.4  170.19
  5211.4   168.9  5214.8   168.9  5334.8   168.2  5344.8   167.8  5880.7   168.3
#Mann= 5 ,-1 , 0
  4333.4      .1       0  4953.8     .08       0  4974.1     .06       0
  5043.8     .08       0  5203.4     .06       0
#XS Ineff= 2 , 0
       0                  5203.4       0  170.19
Permanent Ineff=
       F       T
Bank Sta=4974.1,5043.8
Exp/Cntr=0.3,0.1