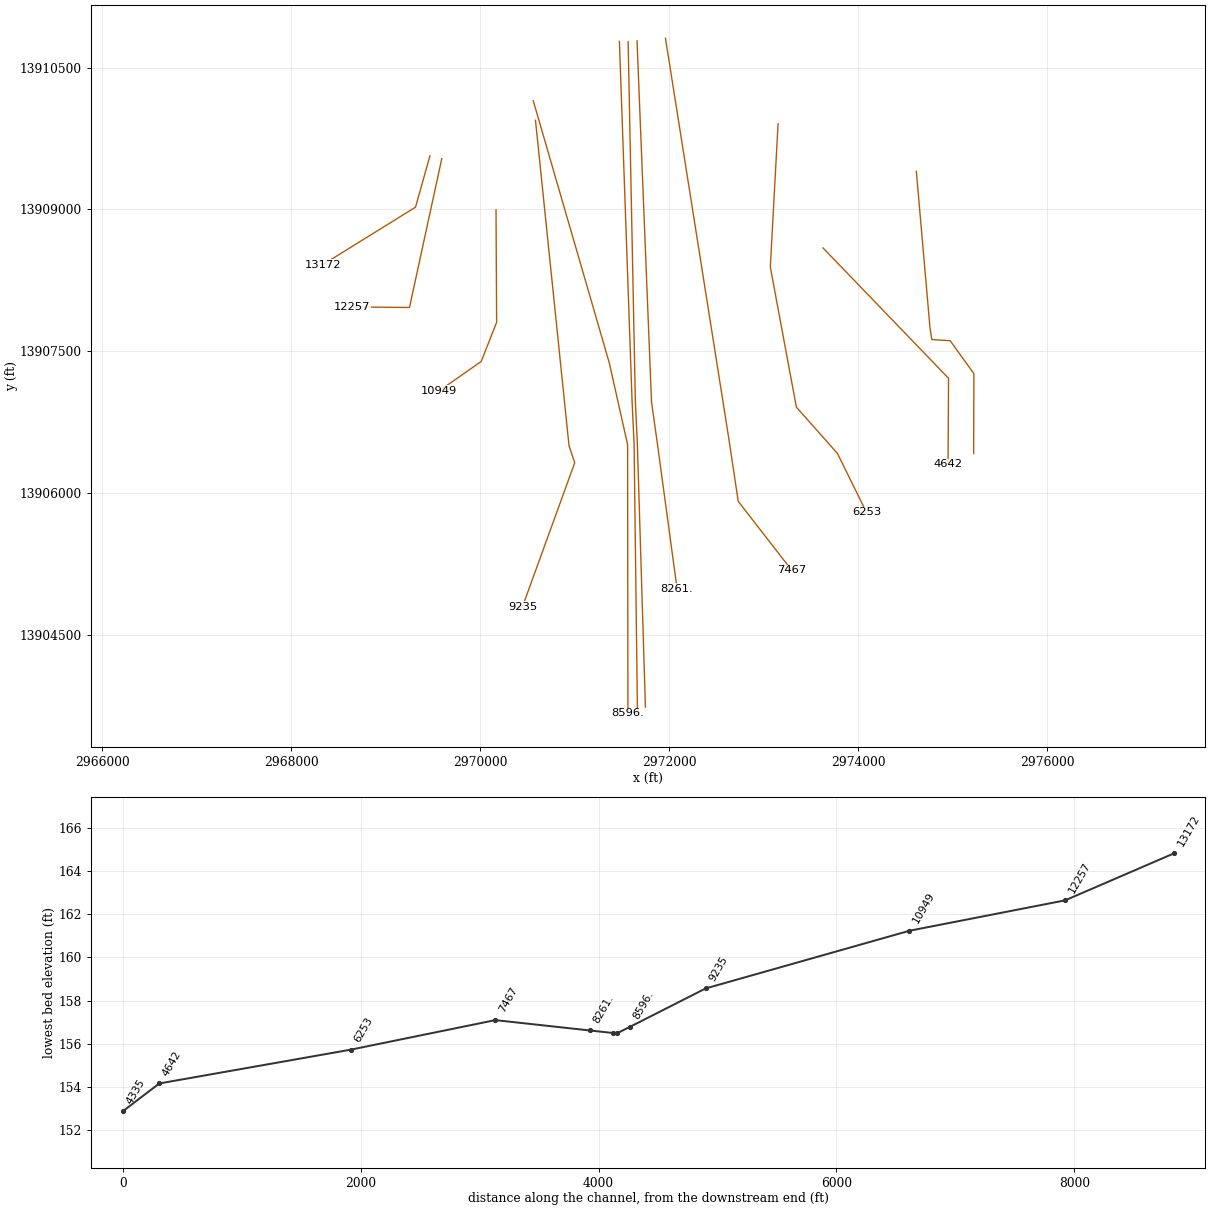
HEC-RAS study K160-00-00.prj: K160-00-00

--- K160-00-00.g02 (geometry) --- (continued)

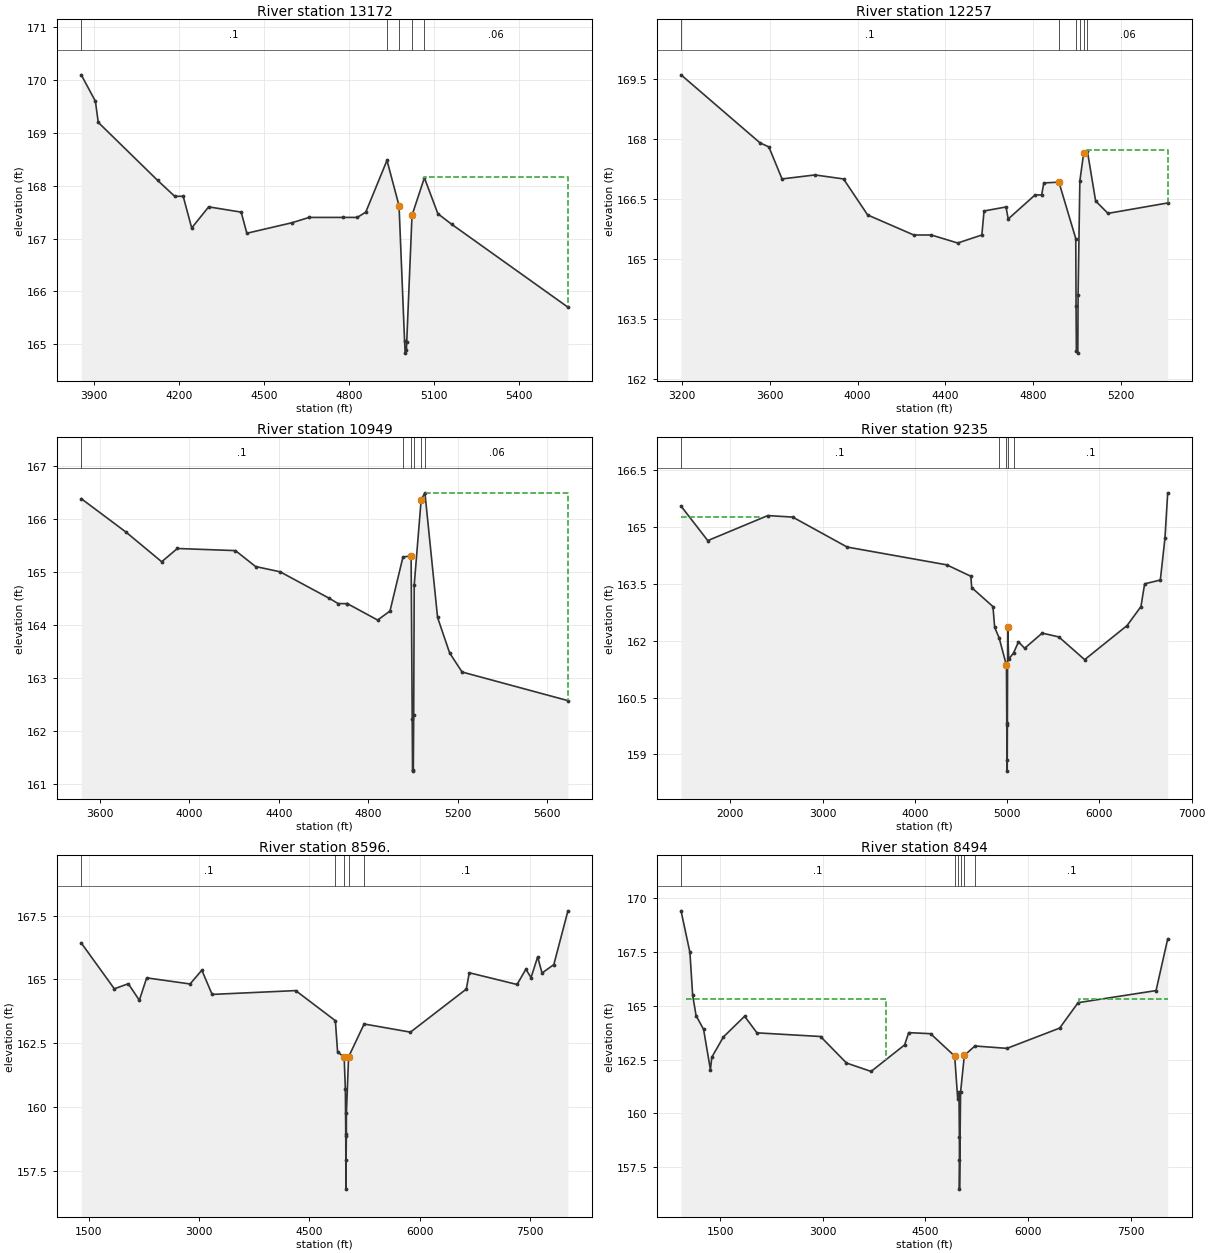
Type RM Length L Ch R = 1 ,13172   ,916,915,562.2
BEGIN DESCRIPTION:
Cross Section K160-00-00-X7
Right overbank spills into K160-01-00.
END DESCRIPTION:
XS GIS Cut Line= 3
 2969468.393525813909568.0937552      2969315.67      13909024.3
      2968335.15     13908415.95
#Sta/Elev= 26
  3854.4   170.1  3904.4   169.6  3914.4   169.2  4124.4   168.1  4184.4   167.8
  4214.4   167.8  4244.4   167.2  4304.4   167.6  4419.2   167.5  4439.2   167.1
  4599.2   167.3  4659.2   167.4  4779.2   167.4  4829.2   167.4  4859.2   167.5
  4934.1  168.48  4976.7  167.62  4996.2  165.06  4998.6  164.83  5002.7  164.89
  5003.8  165.04  5022.5  167.44  5066.2  168.15  5113.8  167.47  5162.6  167.27
  5573.1   165.7
#Mann= 5 ,-1 , 0
  3854.4      .1       0  4934.1     .08       0  4976.7     .06       0
  5022.5     .08       0  5066.2     .06       0
#XS Ineff= 2 , 0
       0                 5064.01       0  168.16
Permanent Ineff=
       F       T
Bank Sta=4976.7,5022.5
Exp/Cntr=0.3,0.1

Type RM Length L Ch R = 1 ,12257   ,1047.2,1308,1318.6
BEGIN DESCRIPTION:
Cross Section K160-00-00-X6
Right overbank spills into K160-01-00.
END DESCRIPTION:
XS GIS Cut Line= 4
 2969593.442388513909537.9025018      2969251.86     13907962.35
      2968887.41     13907965.78      2968647.65     13907968.03
#Sta/Elev= 29
  3196.3   169.6  3556.3   167.9  3596.3   167.8  3656.3     167  3806.3   167.1
  3936.3     167  4046.3   166.1  4256.3   165.6  4336.3   165.6  4456.3   165.4
  4566.3   165.6  4576.3   166.2  4676.3   166.3  4686.3     166  4808.5   166.6
  4838.5   166.6  4848.5   166.9  4917.3  166.92    4994  165.51  4995.3  163.83
  4996.8  162.71  5003.3  162.65  5004.6  164.11  5012.6  166.95  5030.4  167.66
  5046.7   167.7  5084.4  166.45  5140.7  166.14  5412.7   166.4
#Mann= 6 ,-1 , 0
  3196.3      .1       0  4917.3     .08       0    4994     .06       0
  5012.6     .08       0  5030.4     .08       0  5046.7     .06       0
#XS Ineff= 2 , 0
       0                 5045.72       0  167.72
Permanent Ineff=
       F       T
Bank Sta=4917.3,5030.4
Exp/Cntr=0.3,0.1

Type RM Length L Ch R = 1 ,10949   ,927.7,1714,1825.7
BEGIN DESCRIPTION:
Cross Section K160-00-00-X5
Right overbank spills into K160-01-00.
END DESCRIPTION:
XS GIS Cut Line= 4
      2970167.32     13908996.38      2970173.88     13907805.57
      2970011.12     13907391.28      2969567.32     13907080.25
#Sta/Elev= 26
  3515.6  166.38  3715.6  165.75  3875.6  165.19  3945.6  165.44  4205.6   165.4
  4295.6   165.1  4405.6     165  4625.6   164.5  4665.6   164.4  4705.6   164.4
  4706.4   164.4  4841.9  164.09  4897.2  164.26  4955.3  165.28  4991.7   165.3
  4996.7  162.22  4998.2  161.24  5001.6  161.26  5003.3   162.3  5005.6  164.75
  5036.7  166.36  5053.5  166.49  5110.1  164.14  5164.1  163.47  5219.7  163.11
  5693.5  162.57
#Mann= 6 ,-1 , 0
  3515.6      .1       0  4955.3     .08       0  4991.7     .06       0
  5005.6     .08       0  5036.7     .08       0  5053.5     .06       0
#XS Ineff= 2 , 0
       0                 5053.34       0  166.49
Permanent Ineff=
       F       T
Bank Sta=4991.7,5036.7
Exp/Cntr=0.3,0.1

Type RM Length L Ch R = 1 ,9235    ,595.9,639,810.4
BEGIN DESCRIPTION:
Cross Section K160-00-00-X4
END DESCRIPTION:
XS GIS Cut Line= 4
 2970584.830201713909943.5446804      2970939.65      13906499.5
      2971000.15     13906318.01      2970447.75     13904795.09
#Sta/Elev= 30
  1466.8  165.55  1756.8  164.64  2406.8   165.3  2676.8  165.26  3266.8  164.47
  4346.8     164  4606.8   163.7  4616.8   163.4  4846.8   162.9  4865.4  162.35
  4913.1  162.08  4993.1  161.35  4996.9  159.77  4998.5  158.85    5001  158.56
  5003.1  159.84  5006.4  162.35  5017.2  161.51  5070.6  161.68  5123.5  161.97
  5190.4   161.8  5380.4   162.2  5560.4   162.1  5840.4   161.5  6300.4   162.4
  6450.4   162.9  6490.4   163.5  6660.4   163.6  6710.4   164.7  6740.4   165.9
#Mann= 5 ,-1 , 0
  1466.8      .1       0  4913.1     .08       0  4993.1     .06       0
  5006.4     .08       0  5070.6      .1       0
#XS Ineff= 2 , 0
       0 2307.96  165.26  5380.4       0   162.2
Permanent Ineff=
       T       T
Bank Sta=4993.1,5006.4
Exp/Cntr=0.3,0.1

Type RM Length L Ch R = 1 ,8596.   ,171.7,102,84.4
BEGIN DESCRIPTION:
K160-00-00-S01A_Pr Culv. - XS4
END DESCRIPTION:
XS GIS Cut Line= 4
      2970561.19      13910151.4      2971364.75      13907379.2
      2971559.66     13906509.47      2971562.77     13903667.63
#Sta/Elev= 30
  1398.7  166.43  1848.7  164.63  2038.7  164.83  2188.7  164.18  2288.7  165.06
  2878.7  164.82  3038.7  165.36  3178.7  164.41    4315  164.56    4855  163.38
    4885  162.16    4975  161.94 4990.88  160.68  4996.5  158.87 4997.29  157.93
 4997.46  156.77 5004.36  158.95    5005  159.74    5035  161.96  5246.3  163.25
  5876.3  162.93  6636.3  164.62  6676.3  165.26  7326.3   164.8  7446.3   165.4
  7516.3  165.07  7606.3  165.88  7666.3  165.25  7826.3  165.58  8018.2  167.69
#Mann= 5 ,-1 , 0
  1398.7      .1       0    4855     .08       0    4975     .06       0
    5035     .08       0  5246.3      .1       0
Bank Sta=4975,5035
Exp/Cntr=0.5,0.3

Type RM Length L Ch R = 1 ,8494    ,33,34,48.4
BEGIN DESCRIPTION:
Upstream Section of Bridge/Culvert/Weir
END DESCRIPTION:
XS GIS Cut Line= 4
      2971472.75     13910780.05      2971607.04     13906965.69
       2971628.2     13906515.29      2971663.85     13903665.02
#Sta/Elev= 30
   924.5   169.4  1054.5  167.47  1094.5  165.49  1144.5  164.54  1254.5   163.9
  1354.5  162.03  1374.5  162.61  1544.5  163.55  1854.5  164.51  2034.5  163.74
  2964.5  163.57  3344.5  162.34  3704.5  161.95  4194.5  163.18  4254.5  163.75
  4574.5   163.7    4927  162.66  4970.8  160.69  4989.4     161  4995.8  158.92
  4996.7  157.83  4996.9  156.49  5013.3  160.99  5068.1  162.69  5222.3  163.13
  5692.1  163.02  6462.1  163.96  6732.1  165.14  7872.1   165.7  8042.6   168.1
#Mann= 6 ,-1 , 0
   924.5      .1       0    4927     .08       0  4970.8     .06       0
  5013.3     .08       0  5068.1     .08       0  5222.3      .1       0
#XS Ineff= 4 ,-1
  996.54 3916.09   165.3 4978.39 4987.53  160.42 5011.82 5019.64   160.4
 6742.21  8042.6  165.32
Permanent Ineff=
       F       F       F       F
Bank Sta=4927,5068.1
Exp/Cntr=0.5,0.3

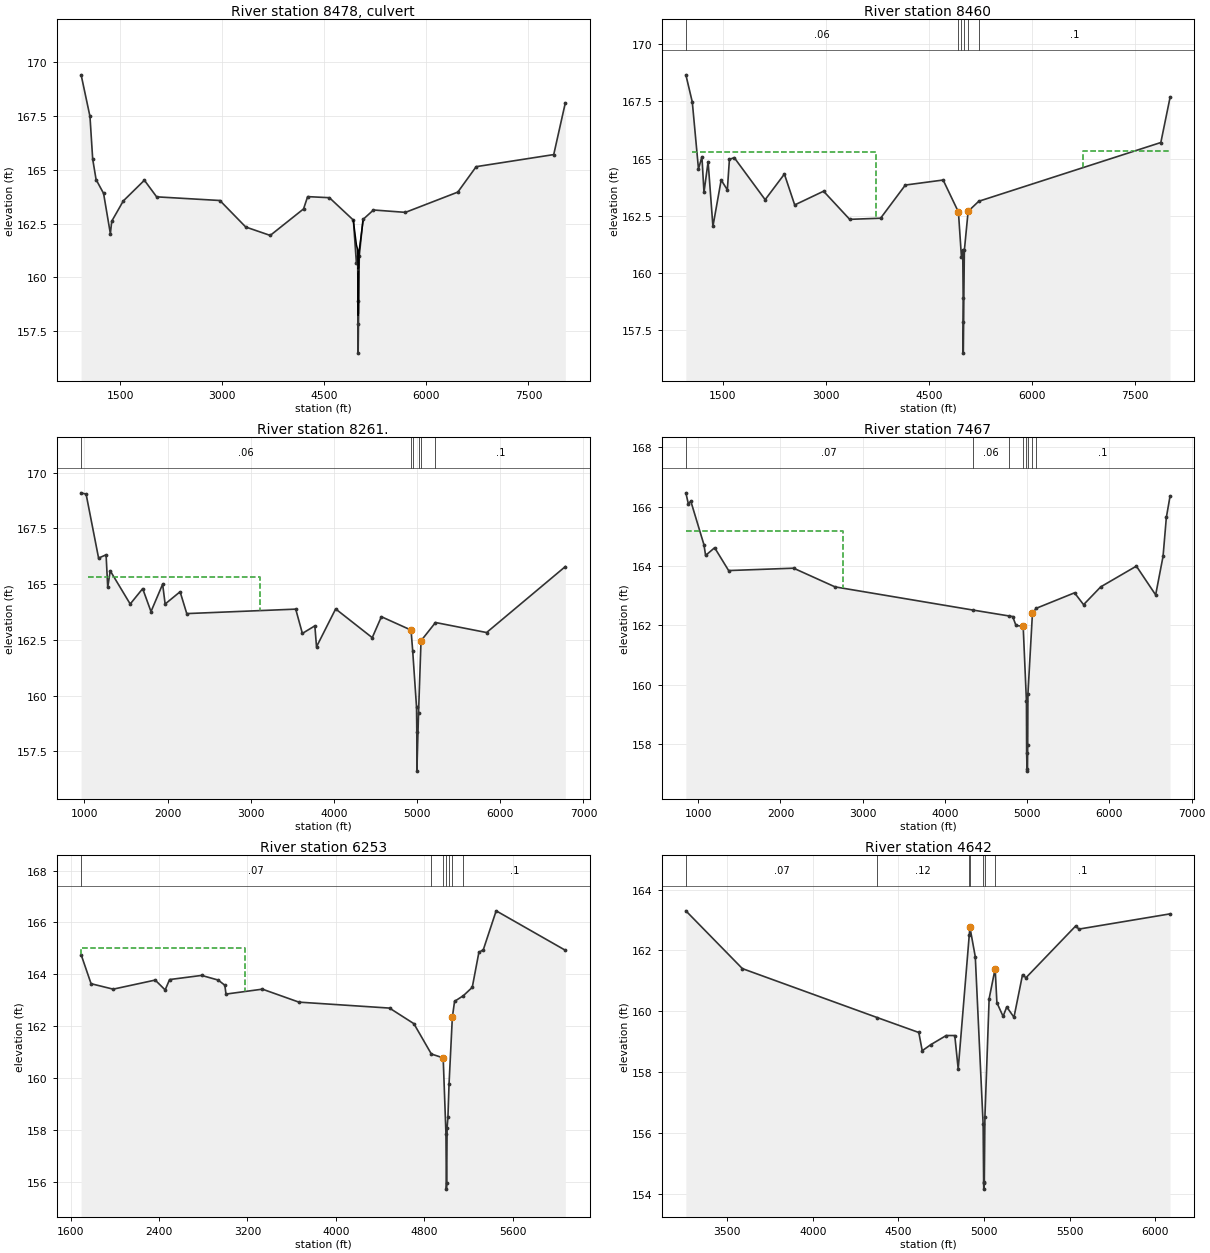
Type RM Length L Ch R = 2 ,8478    ,,,
BEGIN DESCRIPTION:
8468' US CONFLUENCE K100
Structure ID: K160-00-00-S01A
END DESCRIPTION:
Bridge Culvert--1,0,-1,-1, 0
Deck Dist Width WeirC Skew NumUp NumDn MinLoCord MaxHiCord MaxSubmerge Is_Ogee
10,12,2.6,0, 18, 18, , , 0.95, 0, ,,,
    4927    4928  4970.8  4971.6  4989.4  4989.8  4995.8  4996.2  4996.7  4996.9
  4997.3  5001.3  5003.9  5004.3  5004.8    5012  5013.3  5068.1
  162.65   162.6  161.53  161.51   161.3   161.3  160.57  160.52  160.46  160.44
  160.39  160.43  160.45  160.46  160.46  161.22  161.27   162.6
                                                                                
                                                                
    4927    4928  4970.8  4971.6  4989.4  4989.8  4995.8  4996.2  4996.7  4996.9
  4997.3  5001.3  5003.9  5004.3  5004.8    5012  5013.3  5068.1
  162.65   162.6  161.53  161.51   161.3   161.3  160.57  160.52  160.46  160.44
  160.39  160.43  160.45  160.46  160.46  161.22  161.27   162.6
                                                                                
                                                                
BR Coef= 1 , 1 , 1 ,1.25, 0 ,,,0.8,0,2,0,
WSPro=,,,, 1 ,,,, 0 ,,,, 0 ,,,,-1 ,-1 ,-1 , 0 , 0 , 0 , 0 , 0
Culvert=1,2,,12,0.013,0.2,1,1,3,158.22,4998.6,157.63,4998.6,Culvert #1  , 0 ,10
Culvert Bottom n=0.013
Culvert=1,2,,12,0.013,0.2,1,1,3,158.31,5000.9,157.65,5000.9,Culvert #2  , 0 ,10
Culvert Bottom n=0.013
BC Design=,, 0 ,, 0 ,,,,,,
BC HTab HWMax=168.13

Type RM Length L Ch R = 1 ,8460    ,170.8,199,259.7
BEGIN DESCRIPTION:
Downstream Section of Bridge/Culvert/Weir
END DESCRIPTION:
XS GIS Cut Line= 4
      2971565.03      13910775.1      2971641.62     13906967.92
      2971662.84     13906516.14      2971747.86     13903732.22
#Sta/Elev= 30
  960.83  168.66  1054.5  167.47  1144.5  164.54  1194.5  165.08  1224.5  163.52
  1284.5  164.86  1354.5  162.03  1474.5  164.06  1564.5  163.63  1594.5  164.96
  1664.5  165.04  2114.5   163.2  2394.5  164.32  2544.5  162.97  2964.5  163.57
  3344.5  162.34  3794.5  162.39  4154.5  163.84  4704.5  164.06    4927  162.66
  4970.8  160.69  4989.4     161  4995.8  158.92  4996.7  157.83  4996.9  156.49
  5013.3  160.99  5068.1  162.69  5222.3  163.13  7872.1   165.7 8006.27  167.67
#Mann= 6 ,-1 , 0
  960.83     .06       0    4927     .08       0  4970.8     .06       0
  5013.3     .08       0  5068.1     .08       0  5222.3      .1       0
#XS Ineff= 4 ,-1
 1043.25 3721.45   165.3 4977.62 4987.62  158.93 5011.89  5017.9  158.96
 6734.43  8042.6  165.32
Permanent Ineff=
       F       F       F       F
Bank Sta=4927,5068.1
Exp/Cntr=0.5,0.3

Type RM Length L Ch R = 1 ,8261.   ,767.5,794,795
BEGIN DESCRIPTION:
K160-00-00-S01A_Pr Culv. - XS1
END DESCRIPTION:
XS GIS Cut Line= 4
      2971659.25      13910784.4      2971812.54     13906960.97
      2971875.22     13906517.11      2972082.69      13904984.6
#Sta/Elev= 30
   960.6   169.1  1020.6  169.04  1170.6  166.17  1260.6  166.32  1280.6  164.86
  1310.6   165.6  1550.6  164.11  1700.6   164.8  1800.6  163.77  1940.6     165
  1970.6  164.11  2150.6  164.66  2230.6  163.68  3540.6  163.88  3620.6  162.79
  3770.6  163.13  3790.6  162.19  4020.6  163.89  4460.6   162.6  4570.6  163.54
  4927.1  162.94  4947.1     162 4993.11  159.48 4996.61  158.36 4997.26  156.61
  5017.1  159.21  5047.1  162.46    5221  163.28  5835.4  162.83  6781.9  165.79
#Mann= 6 ,-1 , 0
   960.6     .06       0  4927.1     .08       0  4947.1     .06       0
  5017.1     .08       0  5047.1     .08       0    5221      .1       0
#XS Ineff= 1 ,-1
 1043.25    3106   165.3
Permanent Ineff=
       F
Bank Sta=4927.1,5047.1
Exp/Cntr=0.3,0.1

Type RM Length L Ch R = 1 ,7467    ,753.7,1214,1215
BEGIN DESCRIPTION:
Cross Section K160-00-00-X3
END DESCRIPTION:
XS GIS Cut Line= 4
      2971960.15     13910811.78       2972632.2     13906562.59
      2972729.87     13905909.64      2973297.03     13905178.88
#Sta/Elev= 30
     850  166.47     880   166.1     910  166.19    1070  164.72    1090  164.36
    1200  164.62    1370  163.85    2160  163.93  2663.8   163.3    4338  162.52
  4778.9  162.32  4823.8   162.3  4863.8     162 4951.46  161.97    4991  159.44
  4993.6  157.69  4998.7  157.09  5003.7  157.15  5006.5  157.97  5009.2  159.69
  5064.5  162.43    5112  162.58  5575.8   163.1  5685.8   162.7  5893.9   163.3
  6327.8     164  6562.2  163.03  6652.2  164.33  6692.2  165.64  6737.3  166.36
#Mann= 8 ,-1 , 0
     850     .07       0    4338     .06       0  4778.9     .08       0
 4951.46     .08       0    4991     .06       0  5009.2     .08       0
  5064.5     .08       0    5112      .1       0
#XS Ineff= 2 , 0
       0    2756   165.2               0
Permanent Ineff=
       F       F
Bank Sta=4951.46,5064.5
Exp/Cntr=0.3,0.1

Type RM Length L Ch R = 1 ,6253    ,1263.3,1611,1612
BEGIN DESCRIPTION:
INTERP_XS0.5
END DESCRIPTION:
XS GIS Cut Line= 5
      2973151.41      13909907.3      2973069.43     13908390.12
       2973345.1     13906907.43      2973780.18     13906416.19
      2974087.02       13905792.
#Sta/Elev= 30
  1695.4  164.76  1785.4  163.64  1985.4  163.43  2365.4  163.78  2455.4   163.4
  2495.4   163.8  2785.4  163.96  2935.4  163.78  2995.4  163.58  3005.4  163.24
  3334.9  163.43  3664.9  162.93  4484.9   162.7  4704.9   162.1    4863  160.93
 4970.06  160.78    4995  157.86  4998.9  155.72  5001.9  155.94  5005.5  158.09
    5013  158.49    5023  159.77    5053  162.35    5073  162.96    5153  163.18
    5233   163.5    5293  164.85    5333  164.95  5449.2  166.45  6074.7  164.93
#Mann= 7 ,-1 , 0
  1695.4     .07       0    4863     .08       0 4970.06     .08       0
    4995     .06       0    5023     .08       0    5053     .08       0
    5153      .1       0
#XS Ineff= 2 , 0
       0    3174     165               0
Permanent Ineff=
       F       F
Bank Sta=4970.06,5053
Exp/Cntr=0.3,0.1

Type RM Length L Ch R = 1 ,4642    ,352.2,307,253.6
BEGIN DESCRIPTION:
Cross Section K160-00-00-X2
END DESCRIPTION:
XS GIS Cut Line= 4
 2973626.724785913908592.9626807      2973626.73     13908592.94
      2974955.01     13907212.69      2974949.73     13906301.36
#Sta/Elev= 28
  3259.5   163.3  3589.5   161.4    4377  159.79  4619.5   159.3  4639.5   158.7
  4689.5   158.9  4779.5   159.2  4829.5   159.2  4849.5   158.1 4914.16  162.51
  4917.9  162.76  4949.3  161.79    4995  156.29  4998.1  154.35  4998.9  154.15
  5001.9  154.37  5005.5  156.52  5030.1  160.41  5065.3   161.4  5075.4  160.28
  5111.6  159.83    5133  160.14  5175.1   159.8  5225.1   161.2  5245.1   161.1
  5535.1   162.8  5555.1   162.7  6086.4   163.2
#Mann= 7 ,-1 , 0
  3259.5     .07       0    4377     .12       0 4914.16     .08       0
  4917.9     .08       0    4995     .06       0  5005.5     .08       0
  5065.3      .1       0
#XS Ineff= 2 , 0
       0  4917.9  162.76               0
Permanent Ineff=
       T       F
Bank Sta=4917.9,5065.3
Exp/Cntr=0.3,0.1

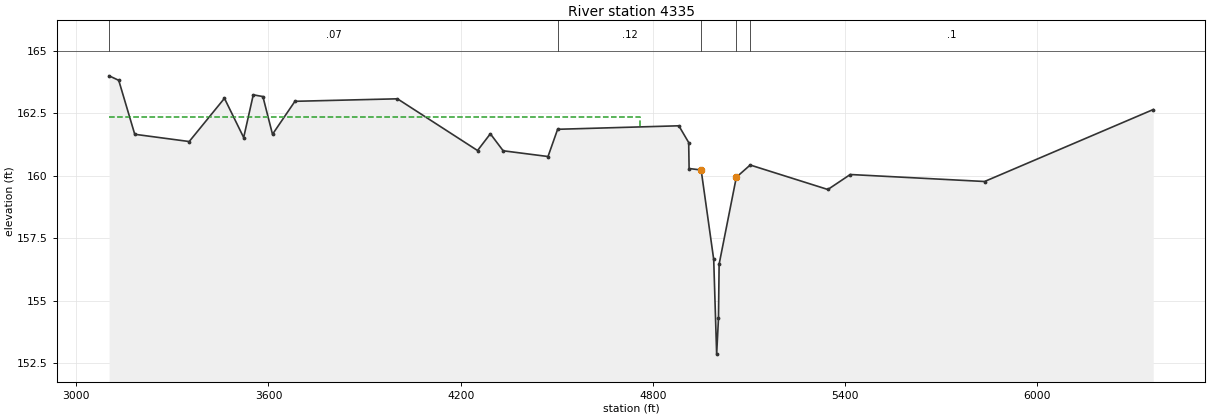
Type RM Length L Ch R = 1 ,4335    ,0,0,0
BEGIN DESCRIPTION:
Cross Section K160-00-00-X1
END DESCRIPTION:
XS GIS Cut Line= 6
       2974614.2      13909403.8      2974758.29     13907751.72
      2974778.06      13907622.5      2974972.12      13907610.5
        2975223.      13907262.3      2975220.57      13906415.9
#Sta/Elev= 30
  3102.7     164  3132.7  163.82  3182.7  161.66  3352.7  161.37  3462.7   163.1
  3522.7  161.53  3552.7  163.24  3582.7  163.17  3612.7  161.66  3682.7  162.98
  4002.7  163.08  4252.7  161.01  4292.7  161.68  4332.7     161  4472.7  160.77
  4502.7  161.86  4881.1     162  4911.8  161.33  4913.1  160.29  4950.7  160.23
  4989.9  156.65  4999.1  152.86  5004.8   154.3  5006.8  156.46  5060.5  159.94
  5103.8  160.43  5346.2  159.45  5416.2  160.05  5835.4  159.77  6361.8  162.65
#Mann= 5 ,-1 , 0
  3102.7     .07       0  4502.7     .12       0  4950.7     .06       0
  5060.5     .06       0  5103.8      .1       0
#XS Ineff= 2 , 0
       0  4761.1  162.37               0
Permanent Ineff=
       F       F
Bank Sta=4950.7,5060.5
Exp/Cntr=0.3,0.1

Chan Stop Cuts=-1
Use User Specified Reach Order=0
User Specified Reach Order=K160-00-00      ,K160-00-00_0043